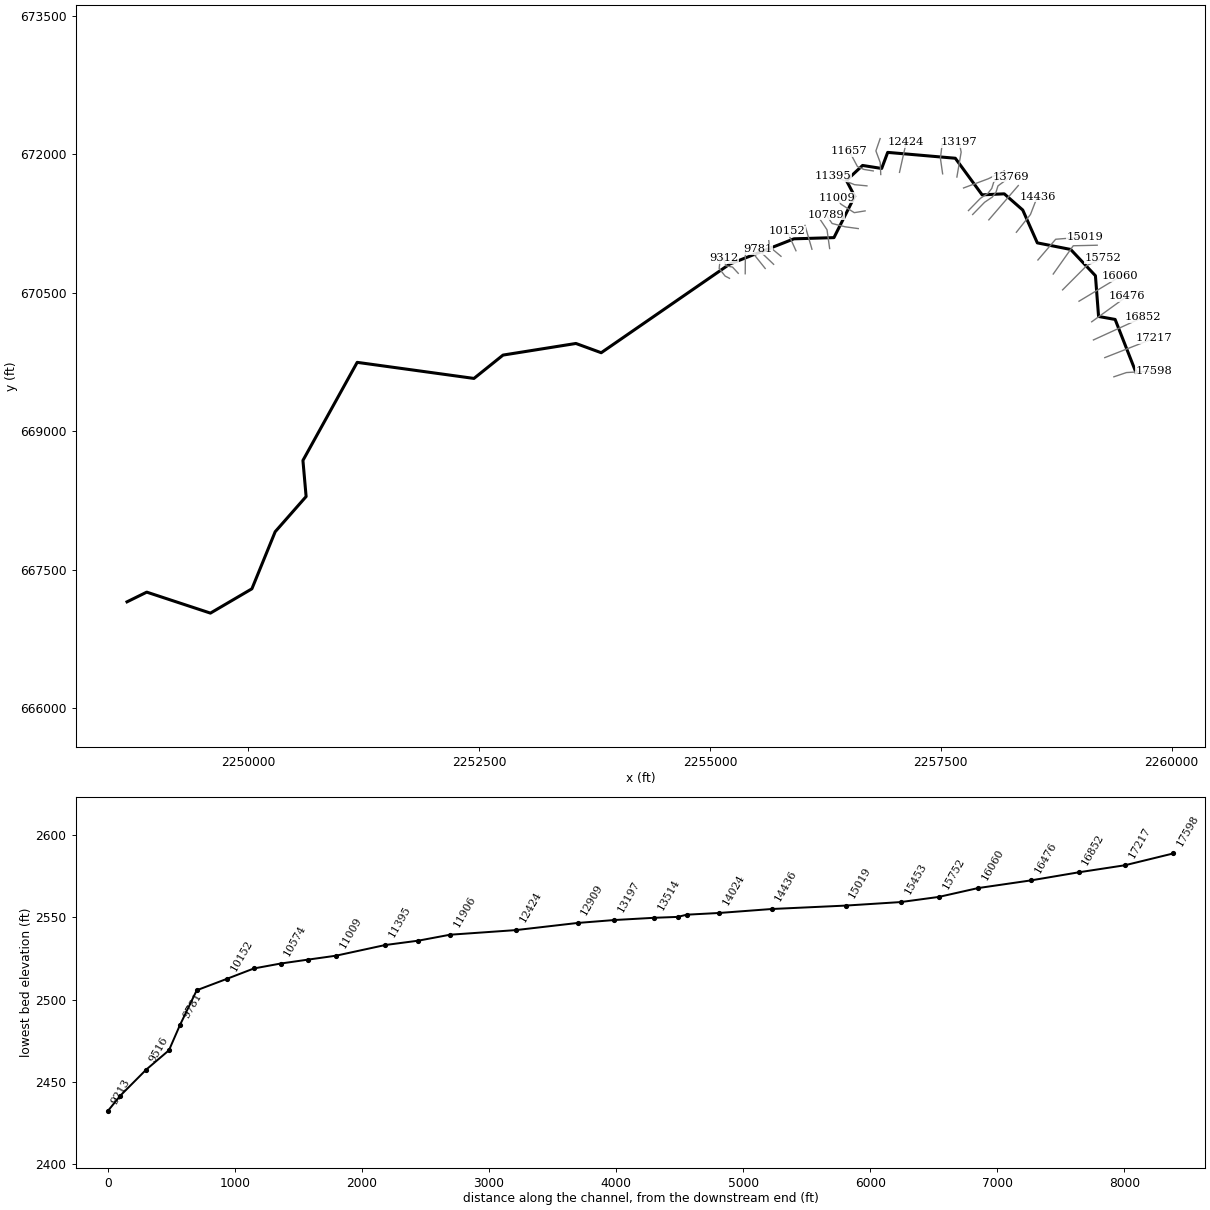
--- CASSITYFK_US.prj (project) ---

Proj Title=CASSITYFK_US
Current Plan=p01
Default Exp/Contr=0,0
English Units
Geom File=g01
Flow File=f01
Plan File=p01
BEGIN DESCRIPTION:
----------MODEL BY WOOD PLC 2022----------
AFH study
Randolph County, WV
HEC-RAS Version: RAS 6.2
Vertical Datum: NAVD88
Projection: NAD 1983 StatePlane West Virginia S FIPS 4702 (US Feet)
Terrain: 1-meter LIDAR (FEMA Region III 3DEP collected 2016-2018)
Land Use: 2019 NLCD
Hydrologic Method:
WV SIR2010-5033 regression equations
Additional Model Notes:
Model was originally CASSITYFK; this is the upper reach from the confluence with PANTHRN. KWSEL tie-in due to coincident peak with PANTHRN and CASSITYFK_US
END DESCRIPTION:
DSS Export Rating Curves= 0
DSS Export Rating Curve Sorted= 0
DSS Export Volume Flow Curves= 0
DXF OffsetX= 0
DXF OffsetY= 0
DXF ScaleX= 0
DXF ScaleY= 0

--- CASSITYFK_US.p01 (plan) ---

Plan Title=Floodplain
Program Version=6.20
Short Identifier=Floodplain
Geom File=g01
Flow File=f01
Subcritical Flow
K Sum by GR= 0
Std Step Tol= 0.01
Critical Tol= 0.01
Num of Std Step Trials= 20
Max Error Tol= 0.3
Flow Tol Ratio= 0.001
Split Flow NTrial= 30
Split Flow Tol= 0.02
Split Flow Ratio= 0.02
Log Output Level= 0
Friction Slope Method= 1
Unsteady Friction Slope Method= 2
Unsteady Bridges Friction Slope Method= 1
Parabolic Critical Depth
Global Vel Dist= 0 , 0 , 0
Global Log Level= 0
CheckData=True
Encroach Param=-1 ,0,0, 0
Mapping Interval=1HOUR
Computation Time Step Use Courant=        0
Computation Time Step Use Time Series=    0
Computation Time Step Count To Double=0
Computation Time Step Max Doubling=0
Computation Time Step Max Halving=0
Computation Time Step Residence Courant=0
Run HTab= 0
Run UNet= 0
Run Sediment= 0
Run PostProcess= 0
Run WQNet= 0
Run RASMapper=-1
UNET Theta= 0
UNET Theta Warmup= 0
UNET ZTol= 0
UNET ZSATol= 0
UNET MxIter= 0
UNET Max Iter WO Improvement= 0
UNET MaxInSteps= 0
UNET DtIC= 0
UNET DtMin= 0
UNET MaxCRTS= 0
UNET WFStab= 0
UNET SFStab= 0
UNET WFX= 1
UNET SFX= 1
UNET Gravity=32.174
UNET 1D Methodology=Finite Difference
UNET DSS MLevel= 1
UNET Pardiso=0
UNET DZMax Abort= 0
UNET Use Existing IB Tables= 0
UNET Froude Reduction=False
UNET Froude Limit= 0
UNET Froude Power= 0
UNET D1 Cores= 0
UNET WindReference=Eulerian
UNET WindDragFormulation=Hsu (1988)
UNET D2 Coriolis=0
UNET D2 Cores= 0
UNET D2 Theta= 1
UNET D2 Theta Warmup= 1
UNET D2 Z Tol= 0.01
UNET D2 Volume Tol= 0.01
UNET D2 Max Iterations= 20
UNET D2 Equation= 0
UNET D2 RampUpFraction=0.1
UNET D2 TimeSlices= 1
UNET D2 Turbulence Formulation=Non-Conservative (original)
UNET D2 Eddy Viscosity=0.3
UNET D2 Transverse Eddy Viscosity=0.1
UNET D2 Smagorinsky Mixing=0
UNET D2 BCVolumeCheck=0
UNET D2 Cores=0
UNET D2 SolverType=PARDISO (Direct)
UNET D2 Minimum Iterations= 2147483647
UNET D2 Maximum Iterations= 2147483647
UNET D2 Restart Number= 10
UNET D2 Relaxation Coeff=1.3
UNET D2 SOR Precondition Iterations= 10
UNET D2 ILUT Maximum Fill= 8
UNET D2 ILUT Tolerance=1E-08
UNET D1D2 MaxIter= 0
UNET D1D2 ZTol=0.01
UNET D1D2 QTol=0.1
UNET D1D2 MinQTol=1
Write IC File= 0
Write IC File at Fixed DateTime=0
Write IC File at Sim End=0
Echo Input=False
Echo Parameters=False
Echo Output=False
Write Detailed= 0
HDF Write Warmup=0
HDF Write Time Slices=0
HDF Flush=0
HDF Compression= 1
HDF Chunk Size= 1
HDF Spatial Parts= 1
HDF Use Max Rows=0
HDF Fixed Rows= 1
Calibration Method= 0
Calibration Iterations= 20
Calibration Max Change=0.05
Calibration Tolerance=0.2
Calibration Maximum=1.5
Calibration Minimum=0.5
Calibration Optimization Method= 1
WQ AD Non Conservative
WQ ULTIMATE=-1
WQ Max Comp Step=1HOUR
WQ Output Interval=15MIN
WQ Output Selected Increments= 0
WQ Output face flow=0
WQ Output face velocity=0
WQ Output face area=0
WQ Output face dispersion=0
WQ Output cell volume=0
WQ Output cell surface area=0
WQ Output cell continuity=0
WQ Output cumulative cell continuity=0
WQ Output face conc=0
WQ Output face dconc_dx=0
WQ Output face courant=0
WQ Output face peclet=0
WQ Output face adv mass=0
WQ Output face disp mass=0
WQ Output cell mass=0
WQ Output cell source sink temp=0
WQ Output nsm pathways=0
WQ Output nsm derived pathways=0
WQ Create Restart=0
WQ Fixed Restart=0
WQ System Summary=0
WQ Write To DSS=0
Sorting and Armoring Iterations= 10
XS Update Threshold= 0.02
Bed Roughness Predictor= 0
Hydraulics Update Threshold= 0.02
Energy Slope Method= 1
Volume Change Method= 1
Sediment Retention Method= 0
Sediment TS Multiplier= 1
Warm Up Method= 0
XS Weighting Method= 0
Number of US Weighted Cross Sections= 1
Number of DS Weighted Cross Sections= 1
Upstream XS Weight=0
Main XS Weight=1
Downstream XS Weight=0
Number of DS XS's Weighted with US Boundary= 1
Upstream Boundary Weight= 1
Weight of XSs Associated with US Boundary= 0
Number of US XS's Weighted with DS Boundary= 1
Downstream Boundary Weight= 0.5
Weight of XSs Associated with DS Boundary= 0.5
Percentile Method= 0
Sediment Output Level= 3
Mass or Volume Output= 0
Output Increment Type= 1
Profile and TS Output Increment= 1
Transport Output Increment 1
XS Output Flag= 0
XS Output Increment= 10
Read HDF5 Sediment Hotstart= 0
Sediment Hotstart Type= 0
Write Gradation File= 0
Read Gradation Hotstart= 0
Write HDF5 File= 1
Write Binary Output= 1
Write DSS Sediment File= 0
DSS Sediment Output Type= 1
SV Curve= 0
Specific Gage Flag= 0
Subcell Erosion Methods= 0
Subcell Deposition Methods= 0
Advection Scheme= 1
Matrix Solver= 0
Implicit Weighting Factor= 1
Maximum Outer Loop Convergence Iterations= 5
Convergence Maximum Absolute= 0.001
Convergence RMSE= 0.0001
Grain Fractions Max Abs Error= 0.001
Max Subgrid Regions= 1
Max Subgrid Length Scale= 3.402823E+38
Initial Layer Thickness= 3.402823E+38
Min Layer Thickness= 3.402823E+38
Max Layer Thickness= 3.402823E+38
Number of Layers= 5

--- CASSITYFK_US.f01 (steady flow) ---

Flow Title=Flow
Program Version=6.20
Number of Profiles= 1
Profile Names=P100yr
River Rch & RM=CASSITYFK_US,Main,17598
     365
River Rch & RM=CASSITYFK_US,Main,13697
     428
River Rch & RM=CASSITYFK_US,Main,10789
     555
River Rch & RM=CASSITYFK_US,Main,7757
     633
River Rch & RM=CASSITYFK_US,Main,4473
    1050
River Rch & RM=CASSITYFK_US,Main,3301
    1170
River Rch & RM=CASSITYFK_US,Main,559
    2720
Boundary for River Rch & Prof#=CASSITYFK_US,Main            , 1
Up Type= 0
Dn Type= 1
Dn Known WS=2099.7
DSS Import GetInterval= 0
DSS Import GetPeak= 0
DSS Import FillOption= 0

--- CASSITYFK_US.g01 (geometry) ---

Geom Title=Geometry
Program Version=6.20

River Reach=CASSITYFK_US    ,Main
Reach XY= 30
     2259614.414      669637.012     2259388.742      670211.936
      2259209.39      670244.112     2259175.362      670685.663
     2258907.191      670970.443     2258545.993      671041.797
      2258387.92      671398.047      2258187.92      671573.307
     2257948.076       671562.37     2257657.712      671959.071
      2256925.42      672022.613     2256860.142      671848.307
     2256653.198      671880.946     2256478.198      671718.099
2256568.01821696671546.434593569     2256343.318      671098.641
2255910.40967608671085.751812552 2255213.9929635670811.779044124
     2253822.525      669851.0812253548.60069322669951.418791526
2252759.12766929669825.5535080112252444.33456007669572.474369137
     2251179.529      669746.747     2250591.837      668683.525
      2250626.37      668292.417     2250291.346      667910.869
2250039.13463472667292.3072275482249589.95895812667028.738952072
2248900.25295812667256.2236826432248686.59214563667151.025957069

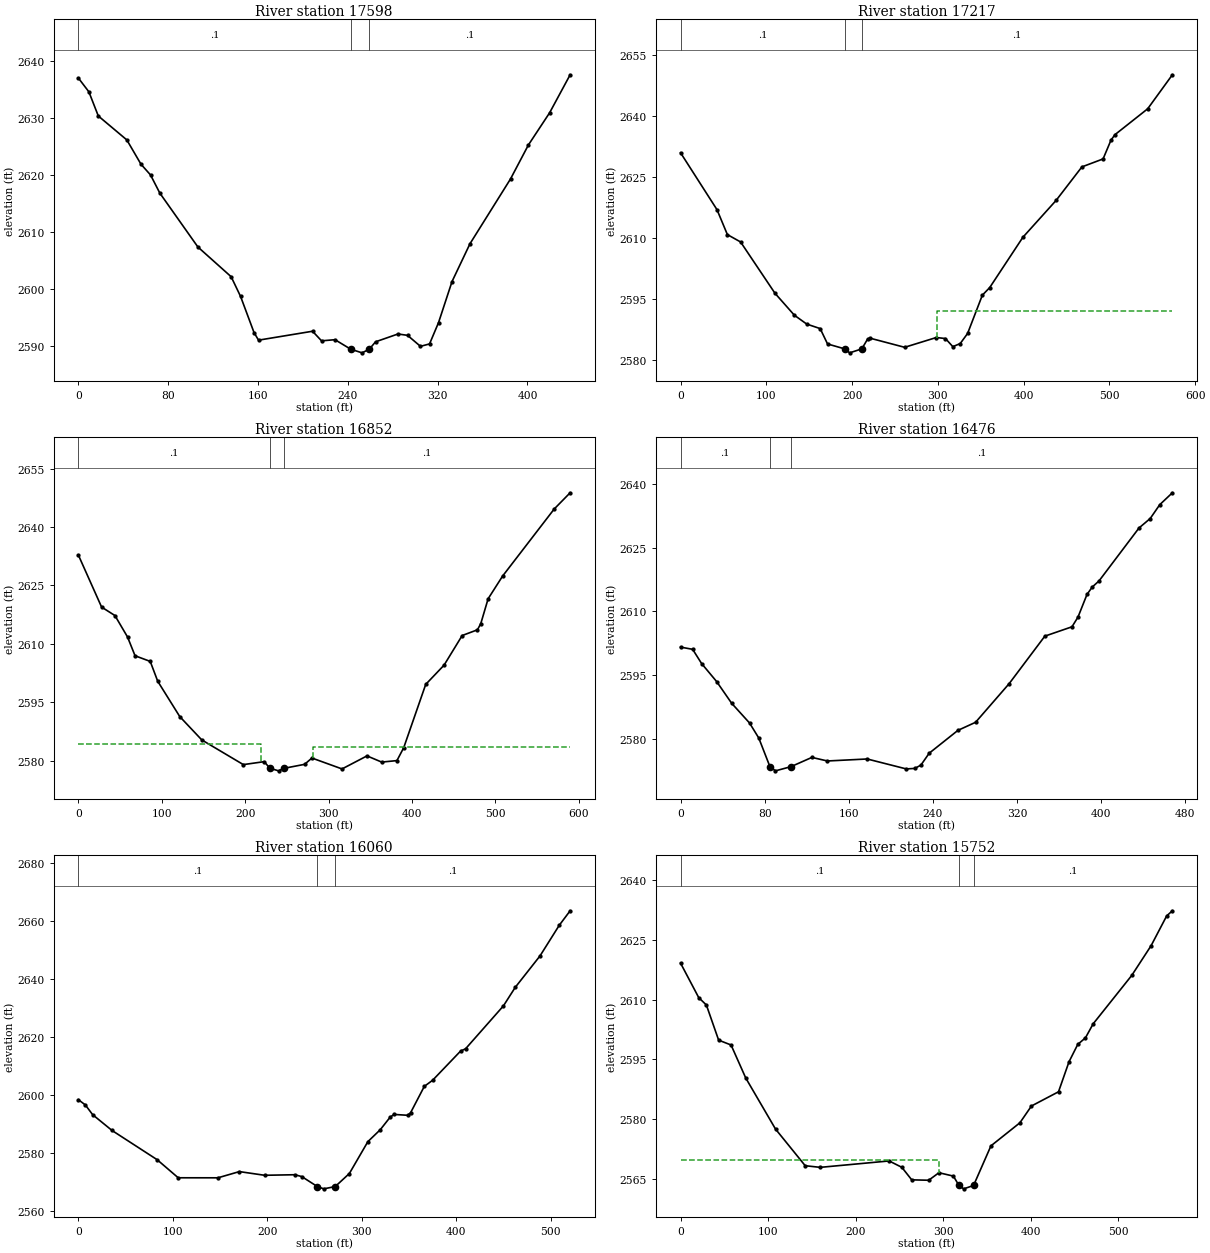
Type RM Length L Ch R = 1 ,17598   ,377.2,380.8,373.9
XS GIS Cut Line= 3
2259375.27523393669590.0966411522259511.26571611669636.124262094
2259805.19202817669653.020021801
#Sta/Elev= 30
       0 2636.96     9.4 2634.54    17.8 2630.31    43.2 2626.12    55.8 2621.87
    64.3 2619.99    72.6 2616.81   106.5 2607.38   136.1 2602.18   144.5 2598.73
   156.5  2592.4   160.5 2591.08   208.6 2592.64   216.6 2590.96   228.6 2591.16
  242.572589.499   252.7 2588.86  259.162589.499   264.7 2590.79   284.7 2592.16
   293.2 2591.92   304.7    2590   312.8 2590.42   320.8 2594.15   332.8 2601.33
   348.8 2607.95   384.9 2619.29   400.9 2625.26   419.7 2630.86     438 2637.52
#Mann= 3 ,-1,0
       0      .1       0  242.57    .045       0  259.16      .1       0
Bank Sta=242.57,259.16
XS Rating Curve= 0 ,0
Exp/Cntr=0.3,0.1

Type RM Length L Ch R = 1 ,17217   ,362.4,365.5,358.7
XS GIS Cut Line= 2
2259276.64000205669797.9877682422259810.39945967670007.717707803
#Sta/Elev= 30
       0 2630.85    42.5 2616.86    54.6 2610.74      70 2608.93   110.1 2596.32
   132.7 2590.93   147.1 2588.75   162.8 2587.64   171.4 2583.86  191.332582.659
   197.2 2581.68   211.4 2582.66   218.1 2585.07   221.2 2585.27   261.3 2583.04
   298.3 2585.45   308.9 2585.19   317.5  2583.2   326.1 2583.96   334.7 2586.44
   351.9 2595.85   360.5 2597.72   399.2 2610.09   437.9 2619.14     468 2627.38
   492.7 2629.34   501.9 2633.95   506.6 2635.31   544.7 2641.66   573.5 2650.02
#Mann= 3 ,-1,0
       0      .1       0  191.33    .045       0   211.4      .1       0
#XS Ineff= 2 , 0
                          299.29         2591.88
Permanent Ineff=
       F       F
Bank Sta=191.33,211.4
XS Rating Curve= 0 ,0
Exp/Cntr(USF)=0,0
Exp/Cntr=0.3,0.1

Type RM Length L Ch R = 1 ,16852   ,369.5,375.3,368.6
XS GIS Cut Line= 2
2259153.59585063669989.5496537022259689.52385584670235.060628351
#Sta/Elev= 30
       0 2632.84    27.9 2619.45    43.9 2617.27      59 2611.76      68 2606.94
    86.2 2605.49    95.2 2600.38   121.6 2591.31     148 2585.31   197.8 2578.97
   222.8 2579.73   229.6 2578.04     240 2577.37   246.1    2578   271.2 2579.04
     280 2580.66   316.1 2577.86     346 2581.21   363.6 2579.62   381.9    2580
     390  2583.3   416.4 2599.58   438.4 2604.53   460.1 2612.14   478.4 2613.61
   482.4  2615.2   491.2 2621.59   508.6 2627.43   570.4 2644.65   589.5 2648.82
#Mann= 3 ,-1,0
       0      .1       0   229.6    .045       0   246.1      .1       0
#XS Ineff= 2 , 0
          218.75  2584.3  281.18         2583.45
Permanent Ineff=
       F       F
Bank Sta=229.6,246.1
XS Rating Curve= 0 ,0
Exp/Cntr(USF)=0,0
Exp/Cntr=0.3,0.1

Type RM Length L Ch R = 1 ,16476   ,413.2,416.5,407.8
XS GIS Cut Line= 2
2259135.03861133670186.4493455982259513.86513322670460.864317286
#Sta/Elev= 30
       0 2601.58    11.5 2601.06      20 2597.72    34.3 2593.48    48.6 2588.37
    65.6 2583.73    74.4 2580.19      852573.458    90.3 2572.47   105.1 2573.46
   124.9 2575.63   139.7 2574.79   177.5 2575.26   214.7 2572.92   222.8 2573.04
   228.6 2573.82   236.5 2576.62   263.8 2581.99   280.6 2583.89   312.6    2593
   346.5 2604.16   372.3 2606.36     378 2608.63   386.6 2613.98   391.6 2615.72
     398 2617.14   436.1 2629.62   446.7 2631.83   455.8 2635.09   467.8 2637.89
#Mann= 3 ,-1,0
       0      .1       0      85    .045       0   105.1      .1       0
Bank Sta=85,105.1
XS Rating Curve= 0 ,0
Exp/Cntr(USF)=0,0
Exp/Cntr=0.3,0.1

Type RM Length L Ch R = 1 ,16060   ,304.1,307.6,307.9
XS GIS Cut Line= 2
2258997.57777806670409.3535499922259443.51105866670677.527185474
#Sta/Elev= 30
       0 2598.52     7.4 2596.72    15.2 2593.34    35.7  2587.9    83.4 2577.84
   105.7 2571.61   147.7  2571.6   170.4 2573.74   197.1 2572.47   229.1 2572.66
   236.4 2572.03  252.962568.582   259.7  2567.8  271.812568.582   286.8 2573.08
   306.4 2584.07   319.5 2588.17   329.8 2592.43     334 2593.44   348.4 2593.14
   351.5 2593.97   366.1  2603.1   374.9 2605.21   404.4 2615.24   409.8 2616.07
   449.8 2630.83   462.3 2637.21   488.5 2648.04   508.9 2658.61   520.4  2663.6
#Mann= 3 ,-1,0
       0      .1       0  252.96    .045       0  271.81      .1       0
Bank Sta=252.96,271.81
XS Rating Curve= 0 ,0
Exp/Cntr(USF)=0,0
Exp/Cntr=0.3,0.1

Type RM Length L Ch R = 1 ,15752   ,296.6,299.6,296.2
XS GIS Cut Line= 3
2258819.62591937670532.2490791932259082.26750355670796.180629397
2259254.22774543 670875.88286562
#Sta/Elev= 30
       0 2619.17    20.8 2610.49    29.5 2608.65    43.5 2599.82    57.7  2598.6
    74.5 2590.29   108.5 2577.47   142.4 2568.26   159.6 2567.85   238.3 2569.46
   252.8 2567.86   264.1 2564.71   283.5 2564.61   295.2  2566.5   311.7 2565.65
  318.092563.298   323.5 2562.45  334.762563.299   354.6 2573.25   387.7 2579.05
   400.9 2583.27   431.8 2586.84   443.8 2594.38   453.8 2598.75   462.6  2600.4
   471.4 2603.92   515.5 2616.09   537.6 2623.56   555.4 2631.05   561.9 2632.33
#Mann= 3 ,-1,0
       0      .1       0  318.09    .045       0  334.76      .1       0
#XS Ineff= 2 , 0
             295 2569.82
Permanent Ineff=
       F       F
Bank Sta=318.09,334.76
XS Rating Curve= 0 ,0
Exp/Cntr=0.3,0.1

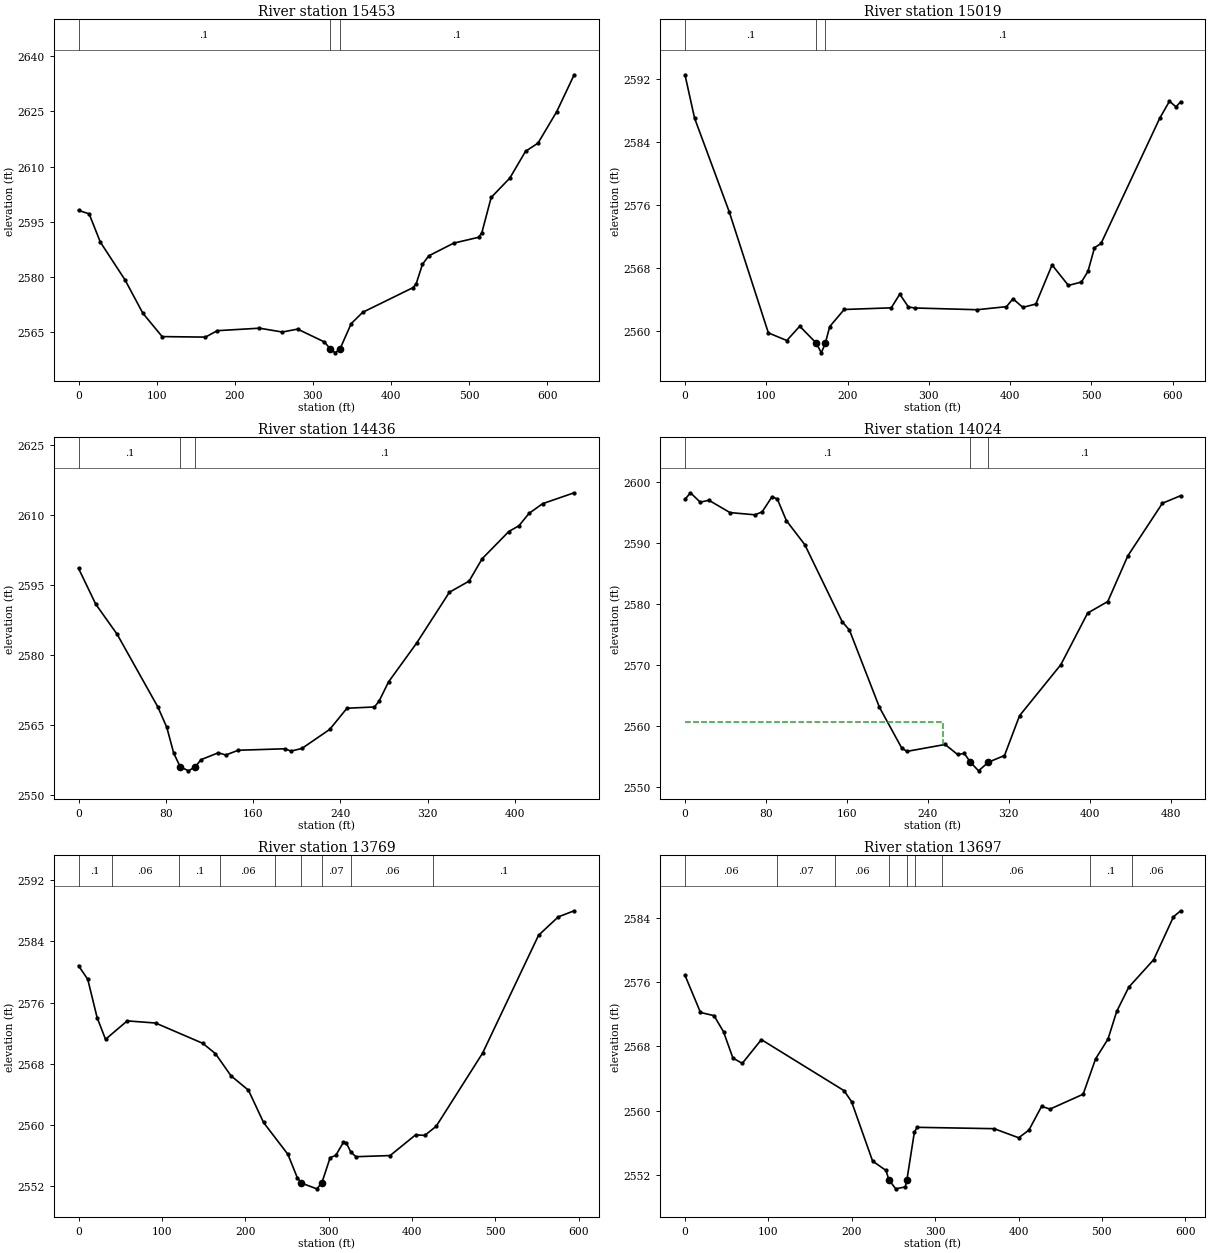
Type RM Length L Ch R = 1 ,15453   ,433.4,433.6,433
XS GIS Cut Line= 3
2258718.29616548670704.127560093 2258935.1162942671010.434838743
2259194.46799011671016.359963235
#Sta/Elev= 30
       0 2598.09    13.6 2597.15    27.9 2589.47    59.5 2579.19    82.4  2570.1
   107.1 2563.74   162.5  2563.6   177.7 2565.35   231.7 2566.03     261 2564.98
   280.6 2565.78   314.9 2562.28  322.052560.469   328.6 2559.32  335.042560.469
   349.2 2567.28   363.9 2570.35   428.4 2577.07   432.4 2578.12   440.4  2583.4
   448.4  2585.7   480.4 2589.17   512.4 2590.77   516.4 2591.95   528.4  2601.6
   552.4  2606.9   572.4 2614.16   588.4 2616.39   612.4 2624.98   634.7 2634.99
#Mann= 3 ,-1,0
       0      .1       0  322.05    .045       0  335.04      .1       0
Bank Sta=322.05,335.04
XS Rating Curve= 0 ,0
Exp/Cntr=0.3,0.1

Type RM Length L Ch R = 1 ,15019   ,576.7,582.9,577.6
XS GIS Cut Line= 3
  2258552.395389670856.3070003662258744.69350351671081.096508662
2259057.82561688 671105.43329967
#Sta/Elev= 30
       0 2592.58    11.8 2587.06    54.4 2575.15   102.6 2559.72   125.3 2558.75
   141.2 2560.57   161.42558.434   167.8 2557.18   172.82558.457   178.1 2560.52
   195.9  2562.7   253.8 2562.91   264.3 2564.65   274.9 2563.02   282.7 2562.89
   359.5 2562.67   395.6 2563.06   403.6 2564.06   415.7 2562.97   431.7 2563.39
   451.7 2568.37   471.8 2565.76   487.9  2566.2   495.9 2567.56   503.9 2570.56
     512 2571.11   584.2 2587.05   596.2 2589.22   604.2 2588.49   609.9 2589.15
#Mann= 3 ,-1,0
       0      .1       0   161.4    .045       0   172.8      .1       0
Bank Sta=161.4,172.8
XS Rating Curve= 0 ,0
Exp/Cntr(USF)=0,0
Exp/Cntr=0.3,0.1

Type RM Length L Ch R = 1 ,14436   ,408.6,411.9,407.7
XS GIS Cut Line= 3
 2258318.9163858671156.7643145192258471.46026444671348.976523559
2258546.99276058671543.862412895
#Sta/Elev= 30
       0  2598.6    15.8  2590.9    35.4 2584.44    72.8 2568.79    80.9 2564.46
    87.3 2558.88   93.192555.989   100.8  2555.1  107.232555.987   112.2 2557.49
   128.2 2558.98     135  2558.5   146.4 2559.52   189.1 2559.84   194.8 2559.34
   204.8 2559.91   230.3    2564   246.1 2568.55   271.3 2568.82   275.6 2570.09
   284.2 2574.19     310 2582.55     340 2593.46   358.1 2595.86     370 2600.65
   394.5 2606.51   403.8 2607.75     413  2610.4   425.4 2612.48   454.4 2614.83
#Mann= 3 ,-1,0
       0      .1       0   93.19    .045       0  107.23      .1       0
Bank Sta=93.19,107.23
XS Rating Curve= 0 ,0
Exp/Cntr=0.3,0.1

Type RM Length L Ch R = 1 ,14024   ,259.7,254.6,253.4
XS GIS Cut Line= 2
2258020.66380808671291.3977464182258339.84762946671662.987472628
#Sta/Elev= 30
       0 2597.09     5.4 2598.17    15.1 2596.63    23.6 2596.95    44.5 2594.93
      69 2594.57    76.2 2595.03      86 2597.52    91.3 2597.15   100.2 2593.62
   118.4 2589.69   155.3 2577.11   162.6  2575.7   192.2 2563.09   214.1 2556.47
   219.3 2555.88   257.1 2557.01   269.4 2555.38   276.1 2555.54  282.142554.109
   290.2  2552.7  299.81 2554.11   315.8  2555.2   330.7 2561.72   371.5 2570.06
     398  2578.5   417.9 2580.39   437.7 2587.85   471.9 2596.46   489.9 2597.69
#Mann= 3 ,-1,0
       0      .1       0  282.14    .045       0  299.81      .1       0
#XS Ineff= 2 , 0
          255.36 2560.68
Permanent Ineff=
       F       F
Bank Sta=282.14,299.81
XS Rating Curve= 0 ,0
Exp/Cntr=0.3,0.1

Type RM Length L Ch R = 1 ,13769   ,68.1,72.3,68.4
XS GIS Cut Line= 6
2257845.51713233 671349.203279782257974.39177341671481.318009314
2258058.96512907671538.7845202142258097.99898553671589.745388371
2258119.68446135671659.1389109682258255.47706533 671759.54574867
#Sta/Elev= 30
       0 2580.82    11.1 2579.04    22.3 2574.04    32.4  2571.2    58.4 2573.61
    92.4 2573.33     149 2570.68   164.2 2569.33   182.9 2566.43   203.8 2564.55
   221.9 2560.33   251.1 2556.17   262.4 2553.11  267.372552.411   285.8 2551.66
  291.712552.412   301.8 2555.75   308.5 2556.03   317.6 2557.72   320.9  2557.7
   326.6 2556.46   332.7 2555.86   373.7 2556.01   404.2 2558.71   415.3 2558.65
   428.9 2559.83   484.5 2569.38   551.7  2584.8   575.3  2587.2   594.4    2588
#Mann= 9 ,-1,0
       0      .1       0      40     .06       0     120      .1       0
     170     .06       0  235.99     .07       0  267.37    .045       0
  291.71     .07       0   326.6     .06       0  425.48      .1       0
Bank Sta=267.37,291.71
XS Rating Curve= 0 ,0
Exp/Cntr=0.3,0.1

Type RM Length L Ch R = 1 ,13697   ,183.4,183.3,180
XS GIS Cut Line= 6
 2257800.1837932671391.9001185552257929.05843429671524.014848089
2258013.63178995671581.4813589892258052.66564641671632.442227146
2258074.35112222671701.8357497432258210.14372621671802.242587445
#Sta/Elev= 30
       0 2576.83    18.6 2572.21    34.8 2571.82    46.2 2569.82    57.5 2566.55
    68.7 2565.89    91.6 2568.84   190.8  2562.5   199.8 2561.13     225 2553.76
   241.1 2552.59  244.422551.458   252.7 2550.31   264.2 2550.55  266.212551.461
   275.1 2557.35   278.4 2557.95   370.7 2557.78   400.2 2556.65   412.5 2557.61
   427.7 2560.56   437.7 2560.21   477.5 2562.06   492.4 2566.45   507.3 2568.91
   517.8 2572.36   532.2 2575.35   562.1 2578.77   585.8 2584.09   594.4 2584.84
#Mann= 9 ,-1,0
       0     .06       0     110     .07       0     180     .06       0
  244.42    .045       0  266.21     .06       0  275.99     .08       0
  308.14     .06       0  485.48      .1       0  535.48     .06       0
Bank Sta=244.42,266.21
XS Rating Curve= 0 ,0
Exp/Cntr=0.3,0.1

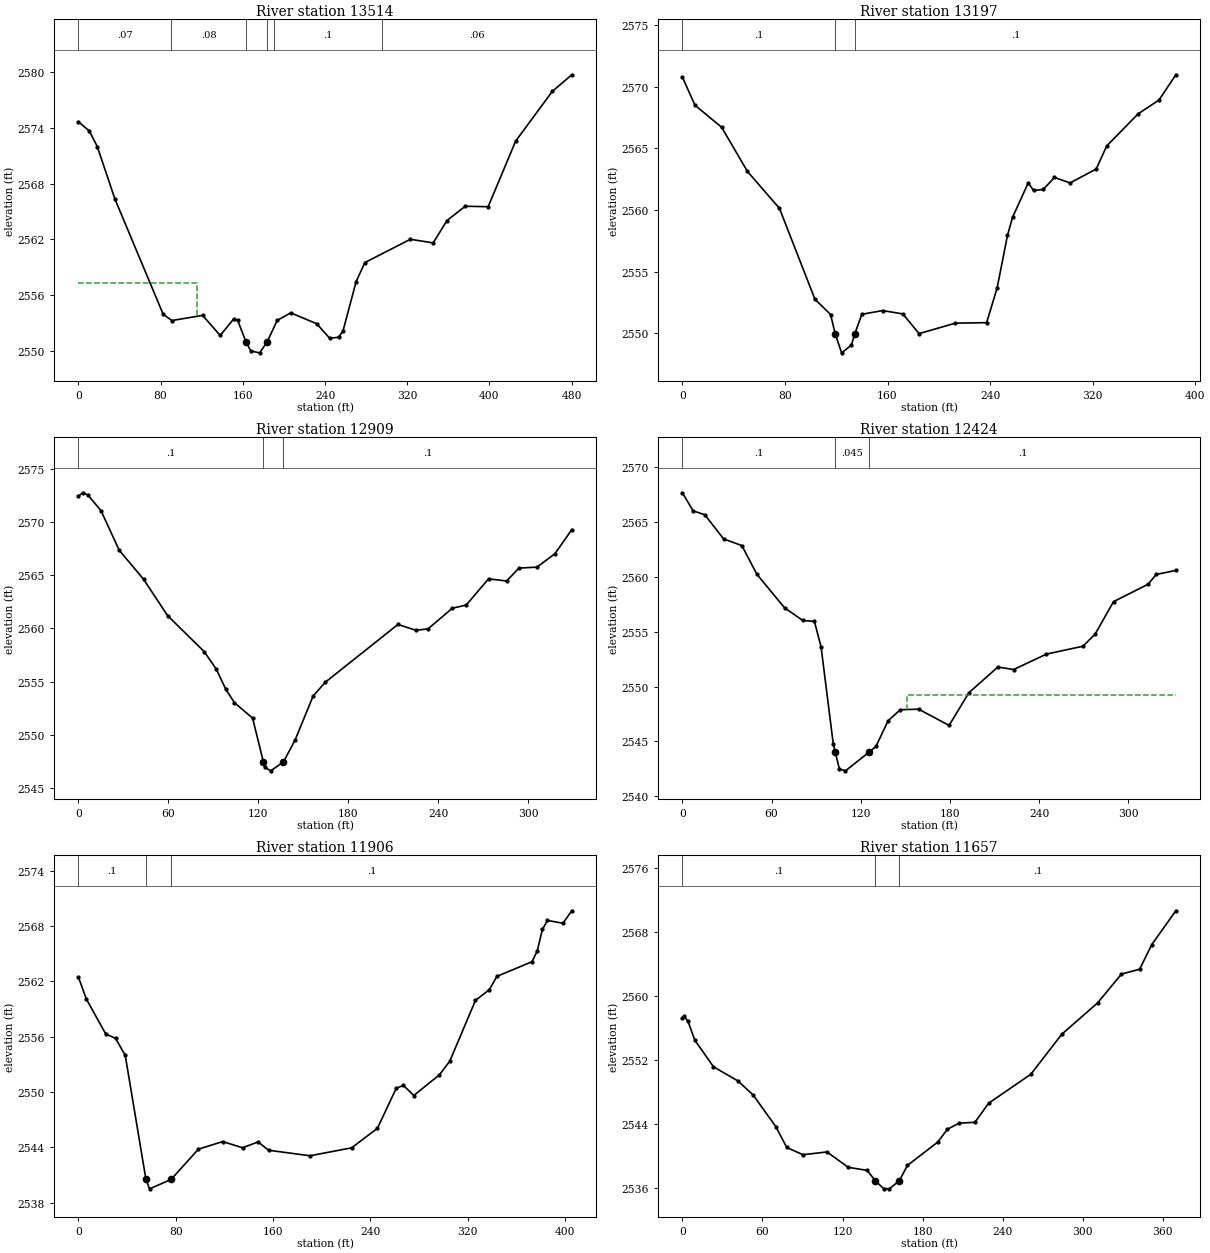
Type RM Length L Ch R = 1 ,13514   ,303.6,317.1,320.3
XS GIS Cut Line= 3
2257746.90043747671636.7793223092258014.71606374671736.532511042
2258189.28414402671822.190140497
#Sta/Elev= 30
       0 2574.68    10.6  2573.7    18.4 2572.01    35.5 2566.37    82.5 2553.94
      91 2553.26   120.9 2553.82     138 2551.65   151.1 2553.43     155 2553.28
  163.042550.979   167.8 2549.98   176.4 2549.78  183.82 2550.98   193.4 2553.27
   206.6 2554.09   231.9 2552.92   244.7 2551.34   253.3 2551.47   257.5 2552.13
   270.3 2557.46   278.8 2559.51   323.1 2562.02   345.3 2561.63   358.7 2564.04
   376.5 2565.58   398.8 2565.53   425.5 2572.59   461.2 2577.96   480.2 2579.75
#Mann= 6 ,-1,0
       0     .07       0      90     .08       0  163.04    .045       0
  183.82     .08       0     190      .1       0  295.79     .06       0
#XS Ineff= 2 , 0
          115.57  2557.3
Permanent Ineff=
       F       F
Bank Sta=163.04,183.82
XS Rating Curve= 0 ,0
Exp/Cntr(USF)=0,0
Exp/Cntr=0.3,0.1

Type RM Length L Ch R = 1 ,13197   ,283.5,287.5,285.3
XS GIS Cut Line= 3
 2257674.8130319671755.2215778952257721.06768953 672025.88716534
2257699.30013662672133.993929822
#Sta/Elev= 30
       0 2570.78     9.8  2568.5    30.6 2566.71    50.7 2563.13    75.7 2560.13
   103.4 2552.75   115.6 2551.51  119.172549.953   124.2  2548.4   131.8 2549.02
  134.522549.951     140 2551.53   156.2 2551.83     172 2551.56   184.6 2549.96
     213 2550.81   237.3 2550.85   245.5 2553.66   253.6 2557.94   257.6 2559.41
   269.8  2562.2   273.9 2561.58   281.5 2561.66   290.2 2562.64   302.4 2562.19
   322.8 2563.32     331 2565.19   355.5  2567.8   371.8 2568.92   384.9 2570.97
#Mann= 3 ,-1,0
       0      .1       0  119.17    .045       0  134.52      .1       0
Bank Sta=119.17,134.52
XS Rating Curve= 0 ,0
Exp/Cntr=0.3,0.1

Type RM Length L Ch R = 1 ,12909   ,485.2,484.9,479.4
XS GIS Cut Line= 3
2257520.46361424671790.262858384 2257496.2691973671958.601912164
2257515.60466955672116.260378283
#Sta/Elev= 30
       0 2572.41     2.9 2572.73     6.4 2572.52    15.1 2571.04    27.2 2567.34
    43.4 2564.62    59.5 2561.19    83.8 2557.83    91.9 2556.18    98.2  2554.3
     104 2553.03   116.1 2551.58  123.332547.459   124.2 2546.96   128.2 2546.63
  136.672547.463   144.4 2549.51   156.5 2553.66   164.6 2554.95     213 2560.37
   225.1 2559.82   233.1 2559.96   249.2 2561.89   258.5 2562.19   273.4 2564.65
   285.5 2564.45   293.6 2565.66   305.7 2565.75   317.7 2567.02   328.9 2569.27
#Mann= 3 ,-1,0
       0      .1       0  123.33    .045       0  136.67      .1       0
Bank Sta=123.33,136.67
XS Rating Curve= 0 ,0
Exp/Cntr(USF)=0,0
Exp/Cntr=0.3,0.1

Type RM Length L Ch R = 1 ,12424   ,506.4,518.3,508.5
BEGIN DESCRIPTION:
IFA placed for spotty FP
END DESCRIPTION:
XS GIS Cut Line= 2
2257053.27051861671806.1094231562257125.48315306672130.090431779
#Sta/Elev= 30
       0 2567.69     7.2 2566.04    15.1 2565.68    27.7 2563.48      40 2562.87
    50.1 2560.25    68.7 2557.19      81 2556.03    88.8 2555.95    93.3  2553.6
   101.5 2544.74  102.742544.035   105.6 2542.47   109.7  2542.3  125.812544.033
   130.2 2544.53   138.4 2546.88   146.6 2547.88   158.9 2547.93   179.4 2546.45
   192.7 2549.43   212.2 2551.78   222.8 2551.55   244.9 2552.96   269.5 2553.68
   277.7  2554.8     290 2557.75   313.3 2559.34   318.7 2560.23   331.9  2560.6
#Mann= 3 ,-1,0
       0      .1       0  102.74    .045       0  125.81      .1       0
#XS Ineff= 2 , 0
                          150.95         2549.23
Permanent Ineff=
       F       F
Bank Sta=102.74,125.81
XS Rating Curve= 0 ,0
Exp/Cntr(USF)=0,0
Exp/Cntr=0.3,0.1

Type RM Length L Ch R = 1 ,11906   ,238.7,249.5,257.5
XS GIS Cut Line= 4
2256850.29446501671782.6891092792256844.43938654671912.476682011
2256797.59875879672038.3608690972256843.46354013672172.051827475
#Sta/Elev= 30
       0 2562.48     6.5  2560.1    22.5 2556.29    30.5 2555.83    38.5 2553.98
   55.532540.507    58.5 2539.49   76.182540.506    98.6 2543.79   118.6 2544.62
   134.9 2543.95   147.7 2544.58   156.3 2543.68   190.4 2543.08   224.6 2543.94
   245.8 2546.06   261.3 2550.41   267.2 2550.72   275.7 2549.62   296.8 2551.87
   305.3 2553.35   326.4 2559.94   337.8 2561.11     344 2562.55   372.9 2564.14
   377.2 2565.32   381.4 2567.64   385.6 2568.62   398.3 2568.32   405.6 2569.67
#Mann= 3 ,-1,0
       0      .1       0   55.53    .045       0   76.18      .1       0
Bank Sta=55.53,76.18
XS Rating Curve= 0 ,0
Exp/Cntr(USF)=0,0
Exp/Cntr=0.3,0.1

Type RM Length L Ch R = 1 ,11657   ,256.9,261.3,260.2
XS GIS Cut Line= 4
2256769.34502081671821.4955323572256666.92732859671837.892839861
2256597.42175865671869.6777761532256508.53357116672037.128602058
#Sta/Elev= 30
       0 2557.23     1.2 2557.51     4.2 2556.85     9.3 2554.49    23.3 2551.16
    41.7 2549.38    53.1 2547.61    70.1 2543.64    78.2 2541.06    90.3 2540.15
   108.3  2540.5   124.3 2538.57   138.5 2538.19   144.5 2536.89   150.7 2535.92
   155.1 2535.88   162.6 2536.91   168.6 2538.81   191.3 2541.73   198.5 2543.33
   207.3  2544.1   219.2 2544.21   229.4 2546.59   261.1 2550.23   284.2 2555.22
   311.1 2559.16     329 2562.77   342.6 2563.37   351.7 2566.46   369.7 2570.69
#Mann= 3 ,-1,0
       0      .1       0   144.5    .045       0   162.6      .1       0
Bank Sta=144.5,162.6
XS Rating Curve= 0 ,0
Exp/Cntr=0.3,0.1

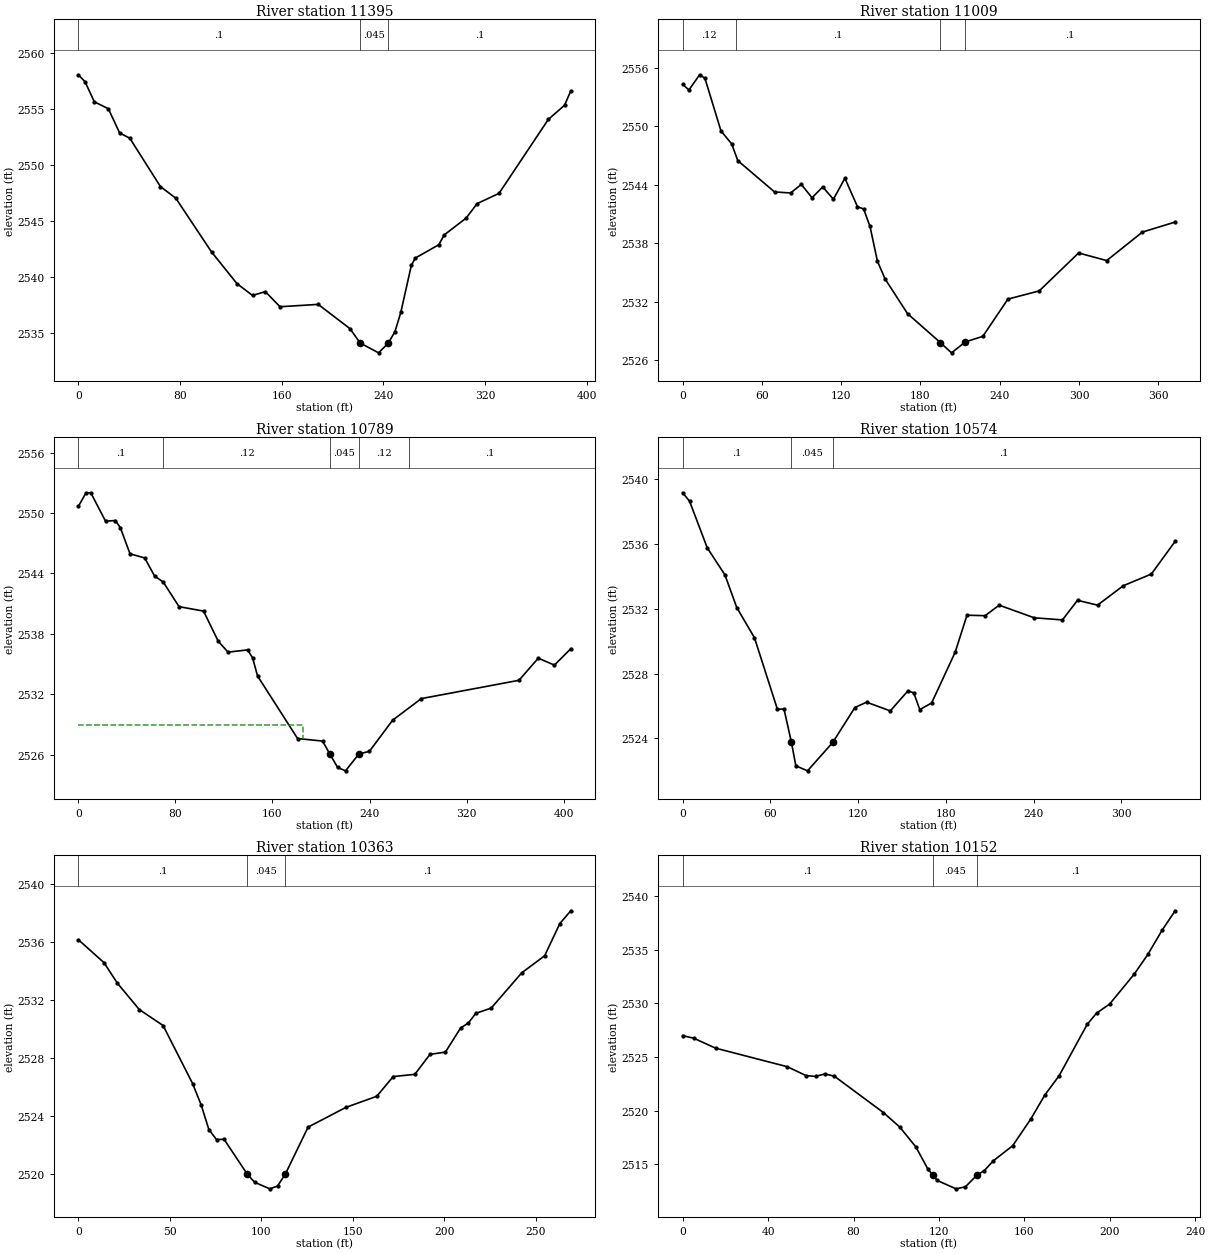
Type RM Length L Ch R = 1 ,11395   ,382.2,386.6,382.7
XS GIS Cut Line= 3
2256700.49849818671659.756378579 2256566.2545927671672.567050445
 2256331.7282442 671766.86542542
#Sta/Elev= 30
       0 2558.07     5.3 2557.44    12.6 2555.65    23.6 2555.04    32.5 2552.87
    40.5  2552.4    64.6 2548.08    76.7 2547.04   104.8 2542.24   124.9  2539.4
   137.1 2538.35   147.2 2538.69   158.7 2537.34   188.8 2537.55   213.8 2535.38
  221.872534.096   236.3 2533.22  243.962534.095   249.2 2535.11   253.8 2536.84
   262.1 2541.04   265.2 2541.69   283.7 2542.88     288 2543.76   305.2 2545.26
   313.9 2546.56   331.1 2547.47   369.9 2554.08   382.7 2555.35   387.6 2556.63
#Mann= 3 ,-1,0
       0      .1       0  221.87    .045       0  243.96      .1       0
Bank Sta=221.87,243.96
XS Rating Curve= 0 ,0
Exp/Cntr=0.3,0.1

Type RM Length L Ch R = 1 ,11009   ,212.1,219.4,219
XS GIS Cut Line= 4
2256680.78008224671388.4843426272256563.27990466671369.148870367
2256419.00753472671461.364199607 2256372.8998701671529.782024526
#Sta/Elev= 30
       0 2554.28     4.7  2553.7    12.8 2555.26    16.8 2554.91      29  2549.5
    37.1 2548.17    41.7 2546.46    69.5 2543.25    81.7 2543.14    89.8 2544.02
    97.9 2542.65     106 2543.76   114.1  2542.5   122.8 2544.65   132.3 2541.74
     137  2541.5   141.8 2539.71   147.4 2536.15   153.2 2534.33   170.2 2530.77
     195 2527.81   203.5 2526.75     214 2527.87   227.2 2528.44   246.2 2532.26
   269.9  2533.1   299.7 2536.99     321 2536.21     348 2539.13   372.8 2540.16
#Mann= 4 ,-1,0
       0     .12       0      40      .1       0     195    .045       0
     214      .1       0
Bank Sta=195,214
XS Rating Curve= 0 ,0
Exp/Cntr(USF)=0,0
Exp/Cntr=0.3,0.1

Type RM Length L Ch R = 1 ,10789   ,227.4,215.4,195.1
XS GIS Cut Line= 4
2256606.41288124671196.6169640482256465.11519934671215.952436308
2256323.81751744671251.6486927882256256.88703654671348.326054087
#Sta/Elev= 30
       0 2550.66     6.3 2552.02    10.3 2552.01    22.4  2549.2    30.5 2549.26
    34.6 2548.56    42.6 2545.95    54.7 2545.54    62.8 2543.75      70 2543.14
      83  2540.7   103.2 2540.26   115.3 2537.26   123.4 2536.18   139.5  2536.4
   143.6 2535.62   147.7 2533.81   180.7 2527.59   201.3 2527.34  207.272526.052
   213.7 2524.72   220.2 2524.38  231.232526.053   239.9 2526.32   259.1 2529.42
   282.7 2531.56   363.2 2533.38   379.1 2535.58   392.4 2534.89   405.9 2536.52
#Mann= 5 ,-1,0
       0      .1       0      70     .12       0  207.27    .045       0
  231.23     .12       0  272.61      .1       0
#XS Ineff= 2 , 0
          184.78 2528.97
Permanent Ineff=
       F       F
Bank Sta=207.27,231.23
XS Rating Curve= 0 ,0
Exp/Cntr(USF)=0,0
Exp/Cntr=0.3,0.1

Type RM Length L Ch R = 1 ,10574   ,208.6,210.6,210.4
XS GIS Cut Line= 3
2256296.67692724670980.567092538 2256268.1885598671183.746833559
2256195.15679536671293.375452482
#Sta/Elev= 30
       0 2539.17     4.7 2538.65    16.8 2535.77    28.9  2534.1      37 2532.08
    49.1 2530.22    64.8  2525.8    69.3 2525.82    74.42523.759    77.4 2522.31
    85.4    2522   102.72523.759   117.8 2525.91   125.8 2526.24     142  2525.7
   154.1 2526.94   158.1 2526.81   162.2 2525.78   170.3 2526.19   186.4 2529.32
   194.5 2531.61   206.9 2531.58   216.5 2532.23   240.5 2531.45   259.8 2531.32
   270.1 2532.53   283.8 2532.23   301.4 2533.43   320.6 2534.15   336.9 2536.17
#Mann= 3 ,-1,0
       0      .1       0    74.4    .045       0   102.7      .1       0
Bank Sta=74.4,102.7
XS Rating Curve= 0 ,0
Exp/Cntr=0.3,0.1

Type RM Length L Ch R = 1 ,10363   ,206.5,211.5,209.8
XS GIS Cut Line= 2
2256105.12524991670972.7583624372256029.59473766671230.967322924
#Sta/Elev= 30
       0 2536.16      14 2534.58    21.3 2533.17    33.3 2531.35    46.3 2530.25
    62.4 2526.26    67.1 2524.78    71.3 2523.09    75.5  2522.4    79.6 2522.42
   92.152520.043    96.3 2519.46   104.6 2519.01   108.8  2519.2  113.132520.042
   125.5 2523.26   146.2 2524.62     163 2525.38     172 2526.74   183.8 2526.89
   192.1 2528.27   200.5 2528.42   208.8 2530.08     213 2530.42   217.1 2531.09
   225.5 2531.45   242.2 2533.88   254.7 2535.05     263 2537.27     269 2538.15
#Mann= 3 ,-1,0
       0      .1       0   92.15    .045       0  113.13      .1       0
Bank Sta=92.15,113.13
XS Rating Curve= 0 ,0
Exp/Cntr(USF)=0,0
Exp/Cntr=0.3,0.1

Type RM Length L Ch R = 1 ,10152   ,235.1,238.1,239.8
XS GIS Cut Line= 2
2255931.85691148670956.490231687 2255837.0876855671166.672883258
#Sta/Elev= 30
       0 2526.99     5.1 2526.76    15.4 2525.83      49  2524.1    57.8 2523.27
    62.2  2523.2    66.6 2523.43      71 2523.22      94 2519.83   101.7 2518.47
   109.2 2516.63   114.8 2514.58  117.072514.022   119.2 2513.51     128 2512.73
   132.4 2512.92  137.842514.023   141.2 2514.42   145.4 2515.33   154.5 2516.74
   163.1 2519.26   169.6 2521.47   176.3 2523.27   189.4 2528.04   193.8 2529.09
   199.9 2529.93   211.4 2532.71   217.8 2534.55   224.5 2536.81   230.6 2538.62
#Mann= 3 ,-1,0
       0      .1       0  117.07    .045       0  137.84      .1       0
Bank Sta=117.07,137.84
XS Rating Curve= 0 ,0
Exp/Cntr=0.3,0.1

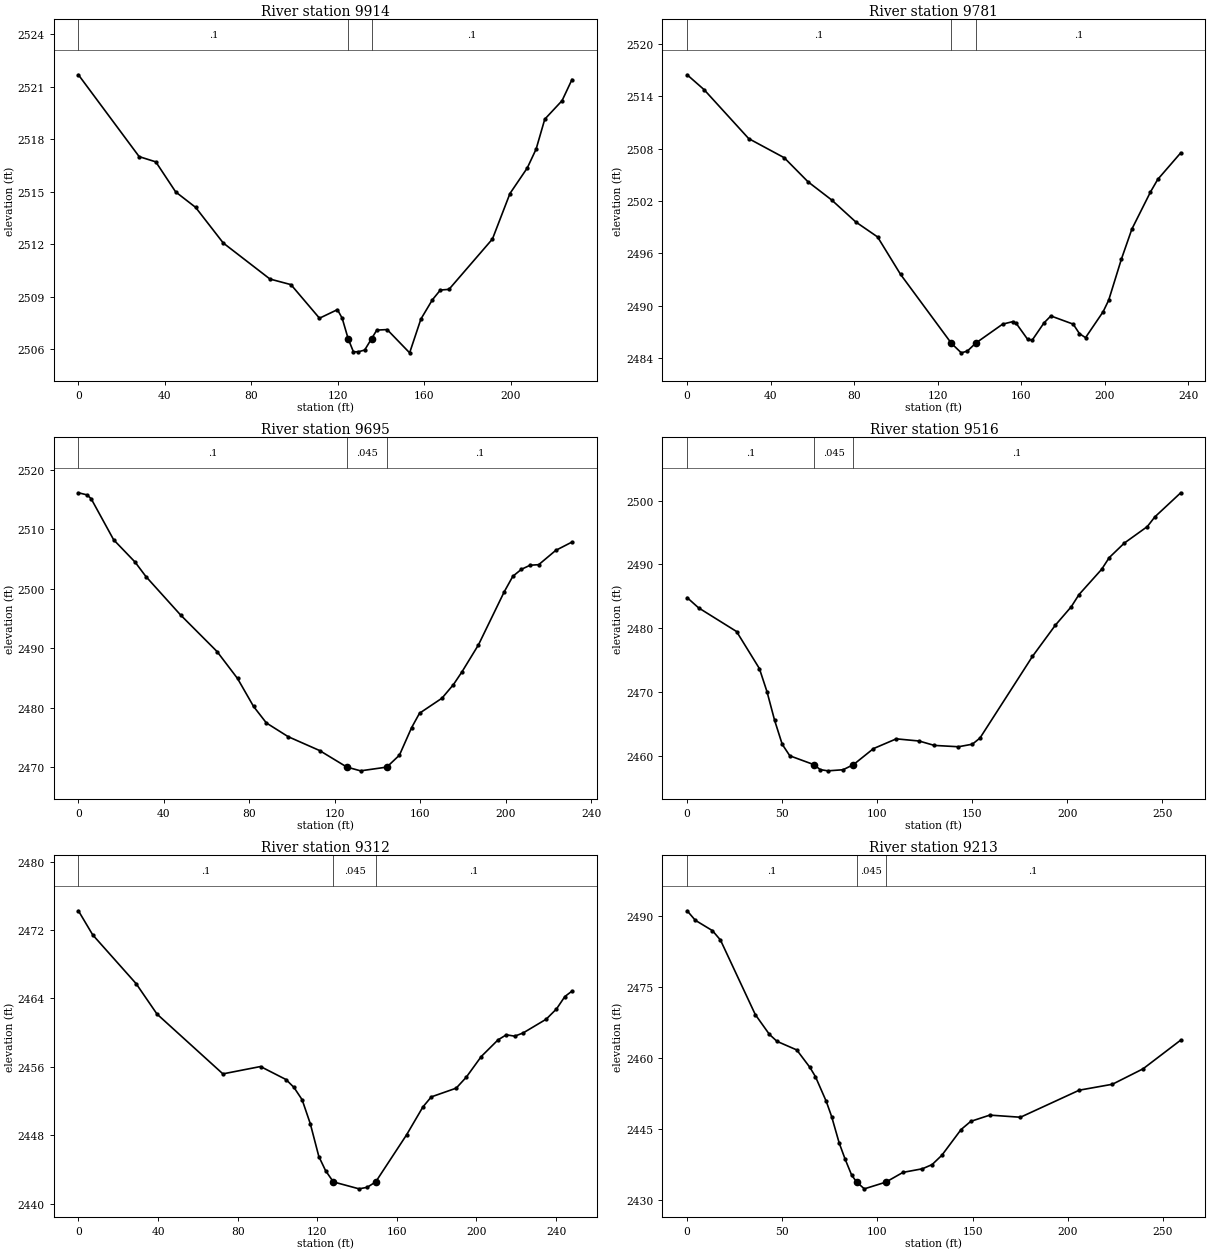
Type RM Length L Ch R = 1 ,9914    ,131.5,132.4,131.1
XS GIS Cut Line= 3
2255769.77816688670896.358611615 2255644.5731689671000.933240613
2255637.45924856671065.669915706
#Sta/Elev= 30
       0 2521.68    28.1    2517    35.8  2516.7      45 2514.98    54.2  2514.1
      67 2512.06    88.6    2510    98.3 2509.68   111.5 2507.76   119.8 2508.25
     122 2507.76   124.82506.573   127.2 2505.84   129.5 2505.84   132.4 2505.94
  135.612506.591     138 2507.08   142.8 2507.11   153.2 2505.78   158.4 2507.71
   163.7 2508.81   167.4 2509.37   171.4 2509.41   191.5 2512.29   199.6 2514.89
   207.6 2516.35   211.7 2517.43   215.7 2519.14   223.7  2520.2   228.3 2521.41
#Mann= 3 ,-1,0
       0      .1       0   124.8    .045       0  135.61      .1       0
Bank Sta=124.8,135.61
XS Rating Curve= 0 ,0
Exp/Cntr(USF)=0,0
Exp/Cntr=0.3,0.1

Type RM Length L Ch R = 1 ,9781    ,88,86.1,89.1
XS GIS Cut Line= 2
 2255690.0379025670809.3430868952255519.21861362670972.800748681
#Sta/Elev= 30
       0 2516.48     8.1 2514.78    29.5 2509.16    46.5 2506.97    57.9 2504.21
    69.2 2502.13    80.8  2499.6    91.2 2497.89   102.2  2493.6   126.62485.679
   131.3  2484.6   134.2  2484.8   138.32485.728   151.1 2487.89     156 2488.18
   157.6 2487.98   163.1 2486.14   165.3 2486.07   170.9 2488.03   174.2 2488.83
   184.9 2487.89   187.9  2486.8   190.8 2486.34   199.2  2489.3   201.9 2490.64
     208 2495.36     213 2498.79   221.9 2503.04   225.4 2504.49   236.4 2507.53
#Mann= 3 ,-1,0
       0      .1       0   126.6    .045       0   138.3      .1       0
Bank Sta=126.6,138.3
XS Rating Curve= 0 ,0
Exp/Cntr(USF)=0,0
Exp/Cntr=0.3,0.1

Type RM Length L Ch R = 1 ,9695    ,181.6,178.9,163.8
XS GIS Cut Line= 3
2255598.72424085670764.4893977272255488.97173324670901.546187714
2255482.54719621 670956.69013056
#Sta/Elev= 30
       0 2516.14     4.1 2515.78       6 2515.12    16.5 2508.23    26.5 2504.49
    31.6 2502.05    47.8 2495.59    64.9 2489.43    74.5 2484.89      82 2480.19
      88 2477.41    98.2  2475.1   112.9 2472.77   125.7 2469.98   132.1 2469.35
   144.4 2469.98   150.3 2471.99     156 2476.62   159.7 2479.04   170.2 2481.57
   175.6 2483.87   179.6 2486.02   187.3 2490.55   199.4  2499.5   203.4 2502.09
   207.4 2503.26   211.5 2503.95   215.5 2504.04   223.5 2506.45   231.1 2507.85
#Mann= 3 ,-1,0
       0      .1       0   125.7    .045       0   144.4      .1       0
Bank Sta=125.7,144.4
XS Rating Curve= 0 ,0
Exp/Cntr(USF)=0,0
Exp/Cntr=0.3,0.1

Type RM Length L Ch R = 1 ,9516    ,188.4,204.5,216.8
XS GIS Cut Line= 2
 2255382.2376043670707.1936397252255384.49038565670966.742821538
#Sta/Elev= 30
       0 2484.78       6 2483.18      26 2479.46      38 2473.65      42 2470.02
      46 2465.53      50 2461.77      54 2459.96    66.72458.568      70 2457.79
      74  2457.6      82 2457.77   87.452458.568      98 2461.09     110 2462.62
     122 2462.28     130 2461.59   142.7 2461.38     150 2461.78     154 2462.74
   181.6 2475.55   193.7 2480.47     202 2483.34   206.1 2485.26     218 2489.22
     222 2491.06   229.9 2493.33     242 2495.92     246 2497.45   259.6 2501.23
#Mann= 3 ,-1,0
       0      .1       0    66.7    .045       0   87.45      .1       0
Bank Sta=66.7,87.45
XS Rating Curve= 0 ,0
Exp/Cntr=0.3,0.1

Type RM Length L Ch R = 1 ,9312    ,105.2,99.1,91.3
XS GIS Cut Line= 4
2255306.75838219670711.8856418092255244.65385762670779.112189021
2255172.30528776670793.8380041252255147.33542737670872.589102288
#Sta/Elev= 30
       0 2474.25     7.2 2471.43      29 2465.73    39.5 2462.17    72.6 2455.18
    91.5 2456.04   104.3 2454.52   108.3  2453.6   112.4 2452.16   116.5 2449.36
   120.8 2445.52   124.2 2443.86   128.1 2442.55     141 2441.74   145.1 2441.92
  149.36 2442.55   164.9 2448.06   173.1 2451.32   177.3 2452.49   189.8 2453.51
   194.9  2454.8   202.4 2457.21   210.8 2459.15     215 2459.75   219.2 2459.59
   223.4 2459.96     235 2461.57   240.2 2462.77   244.4 2464.22     248 2464.86
#Mann= 3 ,-1,0
       0      .1       0   128.1    .045       0  149.36      .1       0
Bank Sta=128.1,149.36
XS Rating Curve= 0 ,0
Exp/Cntr(USF)=0,0
Exp/Cntr=0.3,0.1

Type RM Length L Ch R = 1 ,9213    ,111.9,106.6,103.8
XS GIS Cut Line= 4
2255212.00096326670657.4641512082255164.62225379670681.793758771
 2255099.9567179670764.3863739182255111.48126885670864.906068321
#Sta/Elev= 30
       0 2491.09     4.3 2489.08    13.3 2486.89    17.5 2484.91    35.8 2469.16
    43.2 2464.98    47.2  2463.5    57.6 2461.68    64.5 2457.99    67.4 2456.04
    73.1  2450.8    75.9 2447.61    79.9 2441.99      83  2438.6    86.4 2435.25
   89.092433.744    93.1 2432.33  104.362433.743   113.4 2435.81   123.6 2436.57
   128.7 2437.46   133.8 2439.42   143.9 2444.86     149 2446.59     159 2447.91
   175.1 2447.46     206 2453.18   223.4 2454.43   239.5 2457.69   259.3 2463.76
#Mann= 3 ,-1,0
       0      .1       0   89.09    .045       0  104.36      .1       0
Bank Sta=89.09,104.36
XS Rating Curve= 0 ,0
Exp/Cntr(USF)=0,0
Exp/Cntr=0.3,0.1