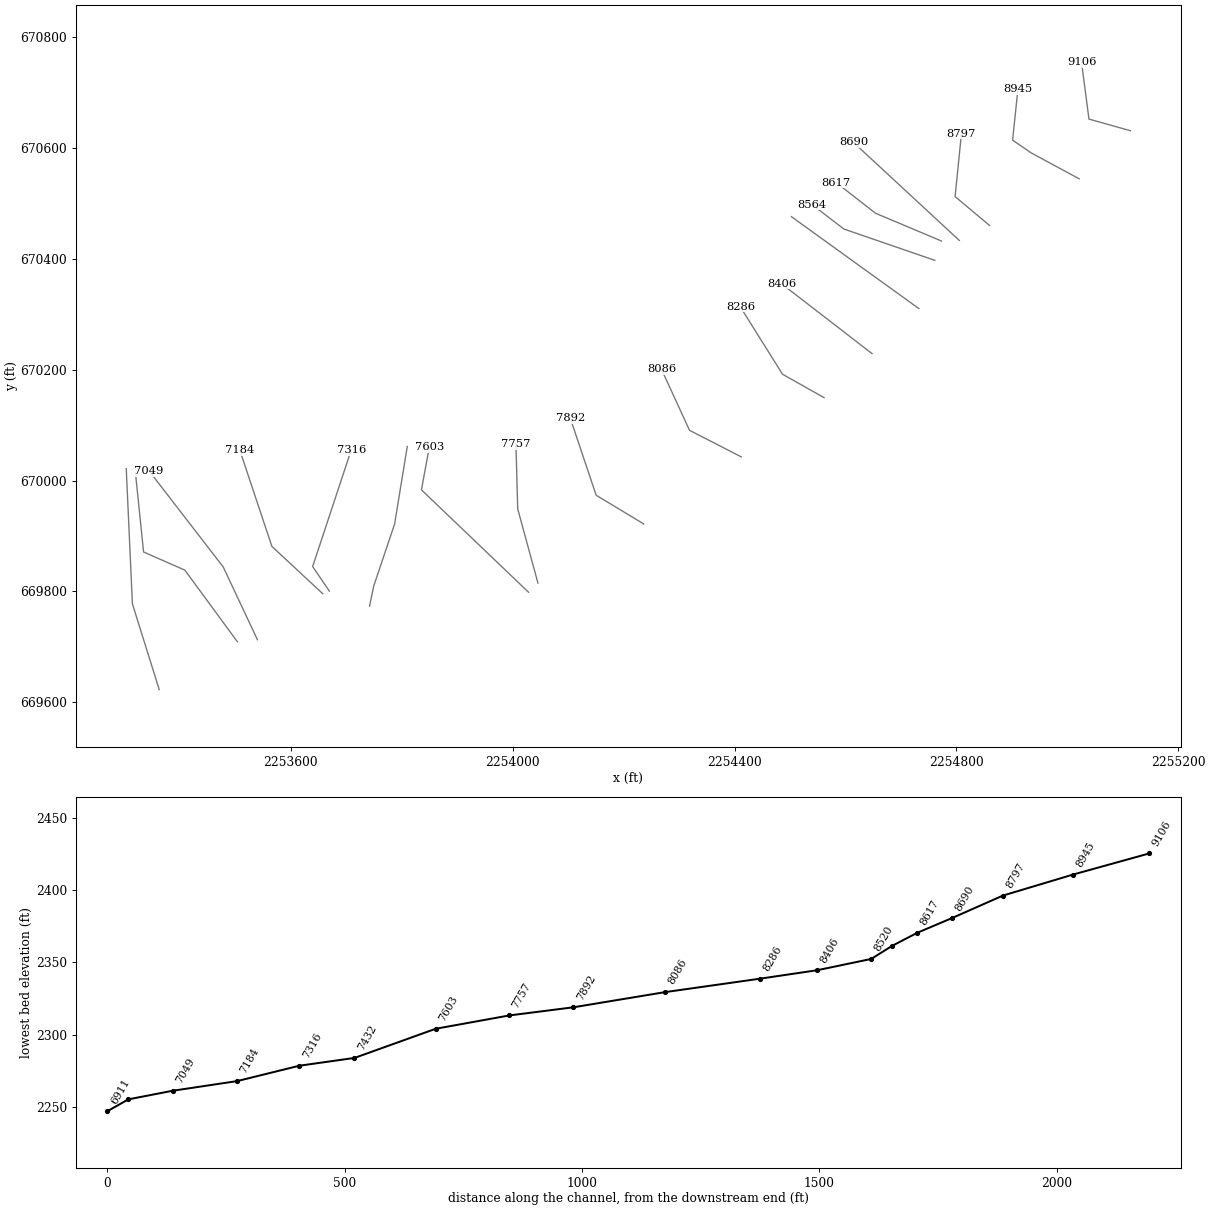
HEC-RAS study CASSITYFK_US.prj: CASSITYFK_US

--- CASSITYFK_US.g01 (geometry) --- (continued)

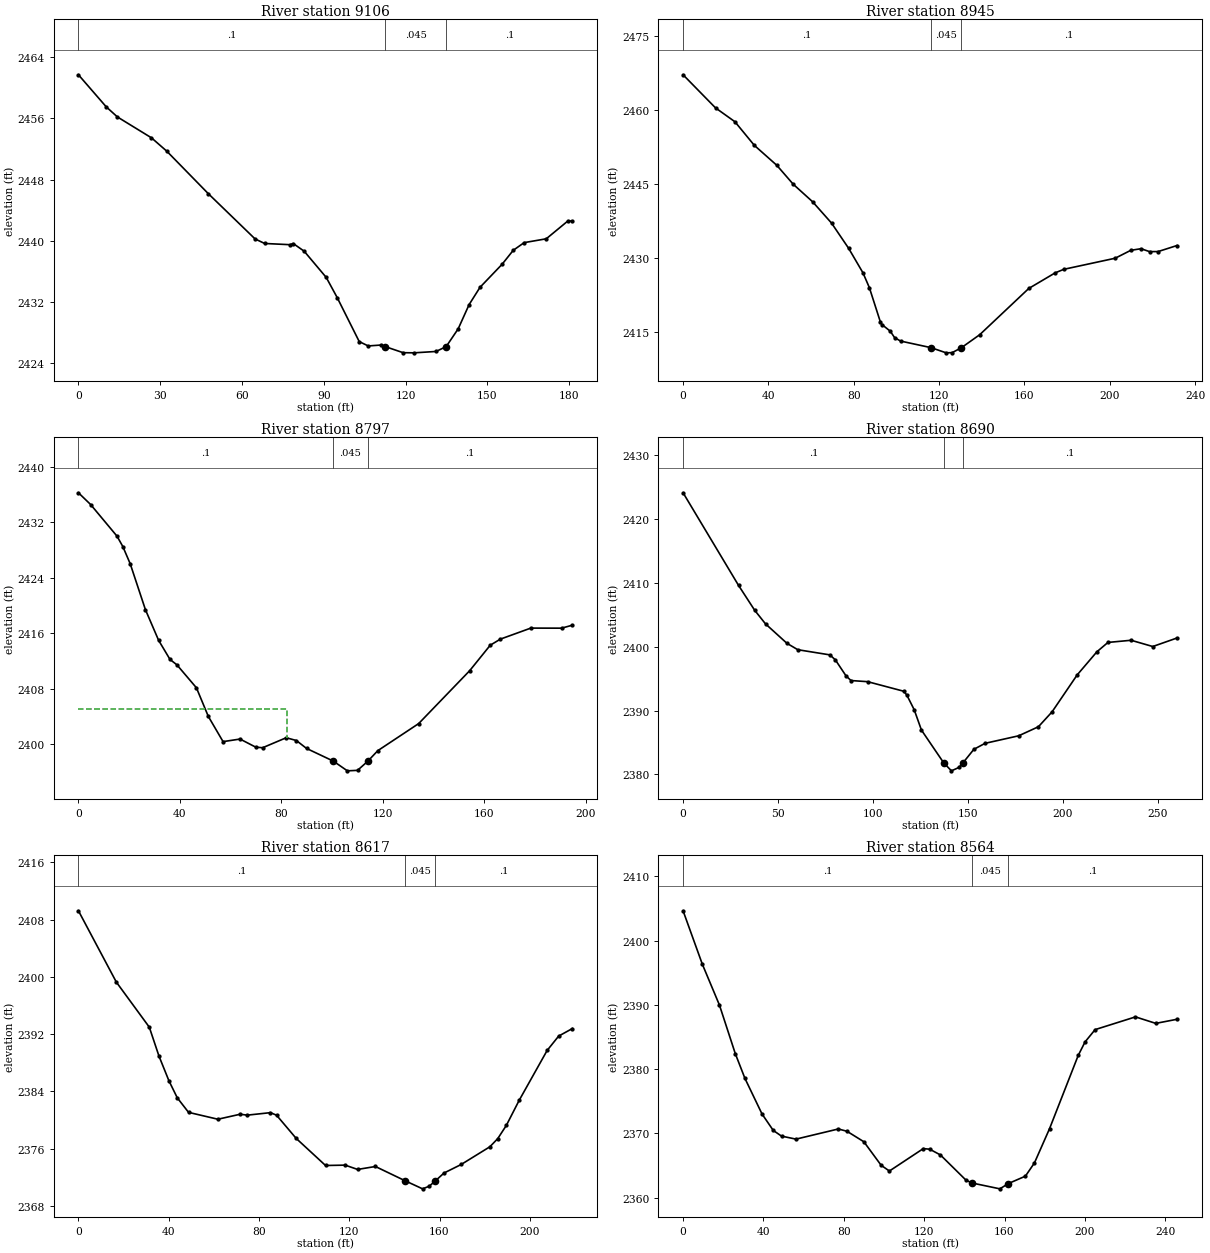
Type RM Length L Ch R = 1 ,9106    ,150.9,160.6,167.3
XS GIS Cut Line= 3
2255113.97422001670631.0750613432255039.23468461670652.045146813
2255025.79232213670754.744796164
#Sta/Elev= 30
       0 2461.71    10.2 2457.52    14.3  2456.2    26.8 2453.47    32.4 2451.73
    47.6 2446.19    64.8 2440.26    68.3 2439.67    77.6 2439.51    78.8 2439.66
    82.8 2438.66    90.9 2435.23    94.9 2432.61     103 2426.85   106.3 2426.28
     111  2426.4  112.522426.196   119.1  2425.4   123.1 2425.38   131.2 2425.56
   134.9  2426.2   139.3 2428.52   143.3 2431.68   147.3 2433.94   155.4 2436.95
   159.5 2438.78   163.5 2439.78   171.6 2440.28   179.6 2442.63   181.2 2442.59
#Mann= 3 ,-1,0
       0      .1       0  112.52    .045       0   134.9      .1       0
Bank Sta=112.52,134.9
XS Rating Curve= 0 ,0
Exp/Cntr(USF)=0,0
Exp/Cntr=0.3,0.1

Type RM Length L Ch R = 1 ,8945    ,153.2,148,138.3
XS GIS Cut Line= 4
2255021.58774976670544.3079037882254935.35847658670590.891780624
2254901.49613643670614.0482701792254911.13515123670706.018156827
#Sta/Elev= 30
       0 2467.12    15.2 2460.41    24.3  2457.6    33.4 2452.81    43.9 2448.78
    51.6 2444.94    60.7 2441.38    69.6 2437.04    77.6 2431.93    84.3 2426.97
    87.3 2423.97    92.5 2416.96    93.2 2416.49    97.1 2415.13    99.1 2413.85
   101.9 2413.14   116.2  2411.8   123.3 2410.75   126.1 2410.79   130.4 2411.78
     139 2414.42     162  2423.8   174.4 2426.97   178.4 2427.68   202.5 2429.93
   209.8 2431.53   214.6 2431.86   218.6 2431.27   222.6 2431.28   231.5 2432.51
#Mann= 3 ,-1,0
       0      .1       0   116.2    .045       0   130.4      .1       0
Bank Sta=116.2,130.4
XS Rating Curve= 0 ,0
Exp/Cntr=0.3,0.1

Type RM Length L Ch R = 1 ,8797    ,101.3,107.6,111.2
XS GIS Cut Line= 3
2254859.81922016 670460.234594752254797.82083576670512.266759721
2254809.23134218670625.435633755
#Sta/Elev= 30
       0 2436.25     4.8 2434.56    15.2    2430    17.5  2428.5    20.4 2426.03
    26.4 2419.41    31.6 2414.99    36.1 2412.23    38.8 2411.46    46.5 2408.15
    51.2 2404.02      57 2400.39    63.7 2400.76    69.9 2399.59    72.6 2399.51
    81.9 2400.95    85.9 2400.55    89.9 2399.41  100.462397.583     106 2396.18
     110 2396.25     114 2397.55     118 2399.09   134.1 2402.99   154.2 2410.61
   162.3 2414.28   166.3 2415.16   178.3 2416.75   190.4 2416.74   194.7 2417.17
#Mann= 3 ,-1,0
       0      .1       0  100.46    .045       0     114      .1       0
#XS Ineff= 2 , 0
           82.29 2405.15
Permanent Ineff=
       F       F
Bank Sta=100.46,114
XS Rating Curve= 0 ,0
Exp/Cntr(USF)=0,0
Exp/Cntr=0.3,0.1

Type RM Length L Ch R = 1 ,8690    ,73,72.9,75.2
XS GIS Cut Line= 2
2254805.43739642670433.139554601 2254614.6420529670609.849335845
#Sta/Elev= 30
       0 2424.12    29.2 2409.61    37.7 2405.71    43.4 2403.58    54.7 2400.53
    60.4 2399.53    77.3 2398.72    80.2 2397.93    85.8 2395.43    88.4  2394.7
    97.2 2394.52   116.2 2393.02   117.8 2392.43   121.7 2390.12   125.5 2386.94
  137.212381.809   141.3 2380.55   145.3 2381.09  147.382381.806   153.1 2383.92
     159 2384.86   176.7 2386.04   187.1 2387.46   194.3  2389.8   207.5 2395.58
   217.9 2399.21   223.7 2400.67   235.9 2401.01   247.3 2400.03   260.1 2401.37
#Mann= 3 ,-1,0
       0      .1       0  137.21    .045       0  147.38      .1       0
Bank Sta=137.21,147.38
XS Rating Curve= 0 ,0
Exp/Cntr(USF)=0,0
Exp/Cntr=0.3,0.1

Type RM Length L Ch R = 1 ,8617    ,51.3,52.8,55.7
XS GIS Cut Line= 3
2254773.11991252670432.172101657 2254654.2894282670482.177690085
 2254583.3137543670537.560223504
#Sta/Elev= 30
       0 2409.23    16.8 2399.27    31.4 2392.98    35.7 2388.93    40.1 2385.49
    43.8 2383.11    48.8 2381.08    61.8 2380.12    71.7 2380.82    74.8 2380.69
    85.1 2381.04    87.8 2380.68    96.5 2377.44   109.5 2373.66   118.2 2373.71
   123.7 2373.11   131.6 2373.52  144.842371.516   152.5  2370.4   155.4 2370.76
   158.2 2371.52     162 2372.61   169.6  2373.8   182.3 2376.27   185.8 2377.41
   189.6 2379.25   195.3 2382.76   207.7 2389.73   212.8 2391.73   218.9 2392.79
#Mann= 3 ,-1,0
       0      .1       0  144.84    .045       0   158.2      .1       0
Bank Sta=144.84,158.2
XS Rating Curve= 0 ,0
Exp/Cntr(USF)=0,0
Exp/Cntr=0.3,0.1

Type RM Length L Ch R = 1 ,8564    ,49.2,44.1,41.3
XS GIS Cut Line= 3
2254761.29063354670397.2219592082254597.29381128670453.679881626
2254539.76049986670497.770830562
#Sta/Elev= 30
       0 2404.63     9.6 2396.31    18.1 2389.97      26 2382.41    30.8 2378.56
    39.3 2373.03    44.9 2370.47      49 2369.59    56.2 2369.12    77.3  2370.7
    81.6 2370.34      90 2368.71    98.6 2365.05   102.7 2364.16   119.6 2367.65
   122.8 2367.55   128.1 2366.66   140.8 2362.75   143.8  2362.3   157.7 2361.39
   161.9 2362.21   170.4 2363.36   174.9 2365.42   182.4 2370.73   196.7 2382.14
   200.1 2384.24   205.1 2386.15   225.2 2388.13   235.3 2387.12   245.9 2387.76
#Mann= 3 ,-1,0
       0      .1       0   143.8    .045       0   161.9      .1       0
Bank Sta=143.8,161.9
XS Rating Curve= 0 ,0
Exp/Cntr(USF)=0,0
Exp/Cntr=0.3,0.1

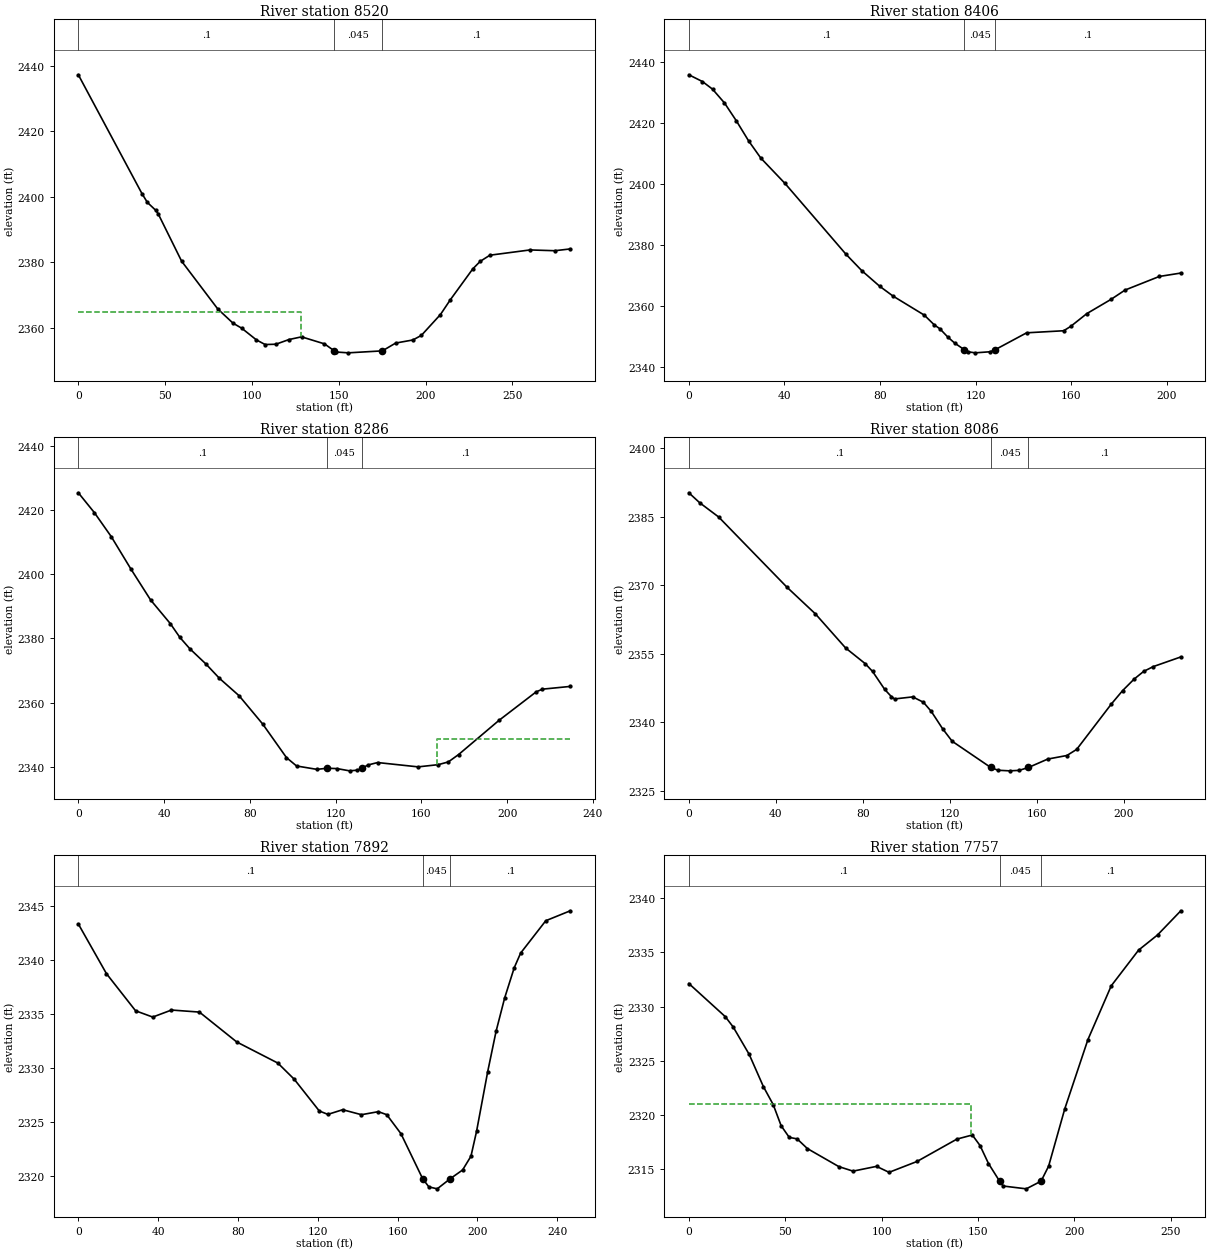
Type RM Length L Ch R = 1 ,8520    ,112.2,113.6,114.7
XS GIS Cut Line= 2
2254732.44857373670310.2110111272254502.59780754670476.036494251
#Sta/Elev= 30
       0 2437.33    36.7 2400.96    39.8 2398.29    44.7 2395.84    46.1 2394.72
    59.5 2380.34    80.3 2365.75    89.1 2361.39    94.1 2359.86   102.6 2356.27
   107.6 2354.86   113.8 2354.95   121.3 2356.38   128.6 2357.21   141.8 2355.06
  147.452352.923   148.6 2352.57   155.5 2352.32  175.162352.923   182.8 2355.31
   192.7 2356.25   197.6 2357.65   208.6 2364.03   214.3 2368.55   227.2 2377.97
   231.5 2380.29   237.1 2382.17   260.2 2383.78   274.5 2383.54   283.4 2384.09
#Mann= 3 ,-1,0
       0      .1       0  147.45    .045       0  175.16      .1       0
#XS Ineff= 2 , 0
          128.44  2364.7
Permanent Ineff=
       F       F
Bank Sta=147.45,175.16
XS Rating Curve= 0 ,0
Exp/Cntr(USF)=0,0
Exp/Cntr=0.3,0.1

Type RM Length L Ch R = 1 ,8406    ,123.4,120.5,118.4
XS GIS Cut Line= 2
2254647.99758118670229.0024791712254485.10515488670354.751697927
#Sta/Elev= 30
       0 2435.91     5.7 2433.68     9.9 2431.19    14.9 2426.66    19.9 2420.74
      25 2414.19    30.1 2408.54    40.2 2400.22    65.7 2376.96    72.3 2371.57
    79.8 2366.43    85.4 2363.19    98.5 2356.92   102.7  2353.7     105 2352.45
   108.4 2349.66   111.2 2347.75  115.252345.542   116.9 2344.86   119.8 2344.53
   126.1 2344.89  128.092345.541   141.3 2351.11   156.8 2351.79   159.7  2353.2
   166.5 2357.43   176.6  2362.1   182.5 2365.17   196.8 2369.63   205.8 2370.75
#Mann= 3 ,-1,0
       0      .1       0  115.25    .045       0  128.09      .1       0
Bank Sta=115.25,128.09
XS Rating Curve= 0 ,0
Exp/Cntr=0.3,0.1

Type RM Length L Ch R = 1 ,8286    ,199.7,199.8,198.3
XS GIS Cut Line= 3
2254561.50106796670149.5075506482254486.59148678670191.764237467
2254410.40139994 670313.41227528
#Sta/Elev= 30
       0 2425.49     7.5 2419.28    15.4 2411.76    24.5 2401.71    33.7 2392.04
    42.9 2384.65    47.4 2380.31      52  2376.8    59.5 2372.05    65.8 2367.57
      75 2362.12      86 2353.29    97.1  2342.8   101.8 2340.19   111.3 2339.13
     116 2339.48   120.7 2339.37   126.5 2338.67   130.2 2338.88  132.21 2339.48
   135.2 2340.51   139.6 2341.26   158.5 2339.91   167.9  2340.6   172.6 2341.45
   177.4 2343.76   196.2 2354.41   213.6 2363.34   216.5 2364.17   229.5 2365.03
#Mann= 3 ,-1,0
       0      .1       0     116    .045       0  132.21      .1       0
#XS Ineff= 2 , 0
                          167.33         2348.65
Permanent Ineff=
       F       F
Bank Sta=116,132.21
XS Rating Curve= 0 ,0
Exp/Cntr(USF)=0,0
Exp/Cntr=0.3,0.1

Type RM Length L Ch R = 1 ,8086    ,194.5,193.7,193.2
XS GIS Cut Line= 3
2254412.32215843670042.5853279392254318.84524516670090.604290233
2254268.26527155670200.727777095
#Sta/Elev= 30
       0 2390.29       5  2388.1    13.7 2384.99    45.1 2369.62    58.2 2363.77
    72.1  2356.3    81.1 2352.87    84.5 2351.16    90.1 2347.21    93.2 2345.62
    94.6 2345.13     103 2345.58   107.9  2344.4   111.5 2342.41   116.7 2338.62
   121.1 2335.87  138.862330.118   142.2 2329.51   147.5 2329.38   151.9 2329.48
  156.232330.118   165.1 2331.96   173.9 2332.74   178.4 2334.08   194.4 2344.05
   199.5 2346.94   204.8 2349.47   209.2 2351.16   213.6 2352.21   226.3 2354.33
#Mann= 3 ,-1,0
       0      .1       0  138.86    .045       0  156.23      .1       0
Bank Sta=138.86,156.23
XS Rating Curve= 0 ,0
Exp/Cntr(USF)=0,0
Exp/Cntr=0.3,0.1

Type RM Length L Ch R = 1 ,7892    ,139.2,135.1,131.7
XS GIS Cut Line= 3
2254236.14341733669921.7522206372254150.51176289 669973.44583466
2254103.85010527670112.446816044
#Sta/Elev= 30
       0 2343.32    14.1 2338.73    28.7  2335.3    37.3 2334.72    46.7 2335.37
    60.7 2335.18    79.4 2332.42     100 2330.47   108.2 2328.98   120.8 2326.04
   125.1 2325.73   132.5 2326.16   141.9  2325.7   150.4 2325.98   154.6  2325.7
   161.7 2323.95  172.572319.795   175.7 2319.03   179.9 2318.85  186.482319.794
   192.6 2320.59   196.8 2321.86   199.6 2324.15   205.2 2329.68   209.4 2333.41
   213.7 2336.49   218.5 2339.28   221.7 2340.63   234.3 2343.62   246.6 2344.54
#Mann= 3 ,-1,0
       0      .1       0  172.57    .045       0  186.48      .1       0
Bank Sta=172.57,186.48
XS Rating Curve= 0 ,0
Exp/Cntr=0.3,0.1

Type RM Length L Ch R = 1 ,7757    ,142.9,154.7,157
XS GIS Cut Line= 3
2254045.50884372669814.9462417482254009.01443237669948.759083342
2254005.81316822 670065.28509851
#Sta/Elev= 30
       0 2332.12    18.9 2329.07      23 2328.12    31.3  2325.6    38.7 2322.62
    43.8 2320.96    47.9 2319.02    52.1 2317.95    56.2 2317.81    61.5 2316.92
    77.8 2315.26    85.2 2314.84    97.4 2315.28   103.9 2314.73   118.4 2315.73
   139.1 2317.79   147.1 2318.17   151.1  2317.2   155.5 2315.54  161.252313.919
   163.1 2313.47   175.1 2313.21  182.792313.918   186.7  2315.3   195.1 2320.59
   207.1 2326.96   219.2 2331.91   233.4  2335.2   243.2 2336.59   255.3 2338.82
#Mann= 3 ,-1,0
       0      .1       0  161.25    .045       0  182.79      .1       0
#XS Ineff= 2 , 0
          146.54    2321
Permanent Ineff=
       F       F
Bank Sta=161.25,182.79
XS Rating Curve= 0 ,0
Exp/Cntr(USF)=0,0
Exp/Cntr=0.3,0.1

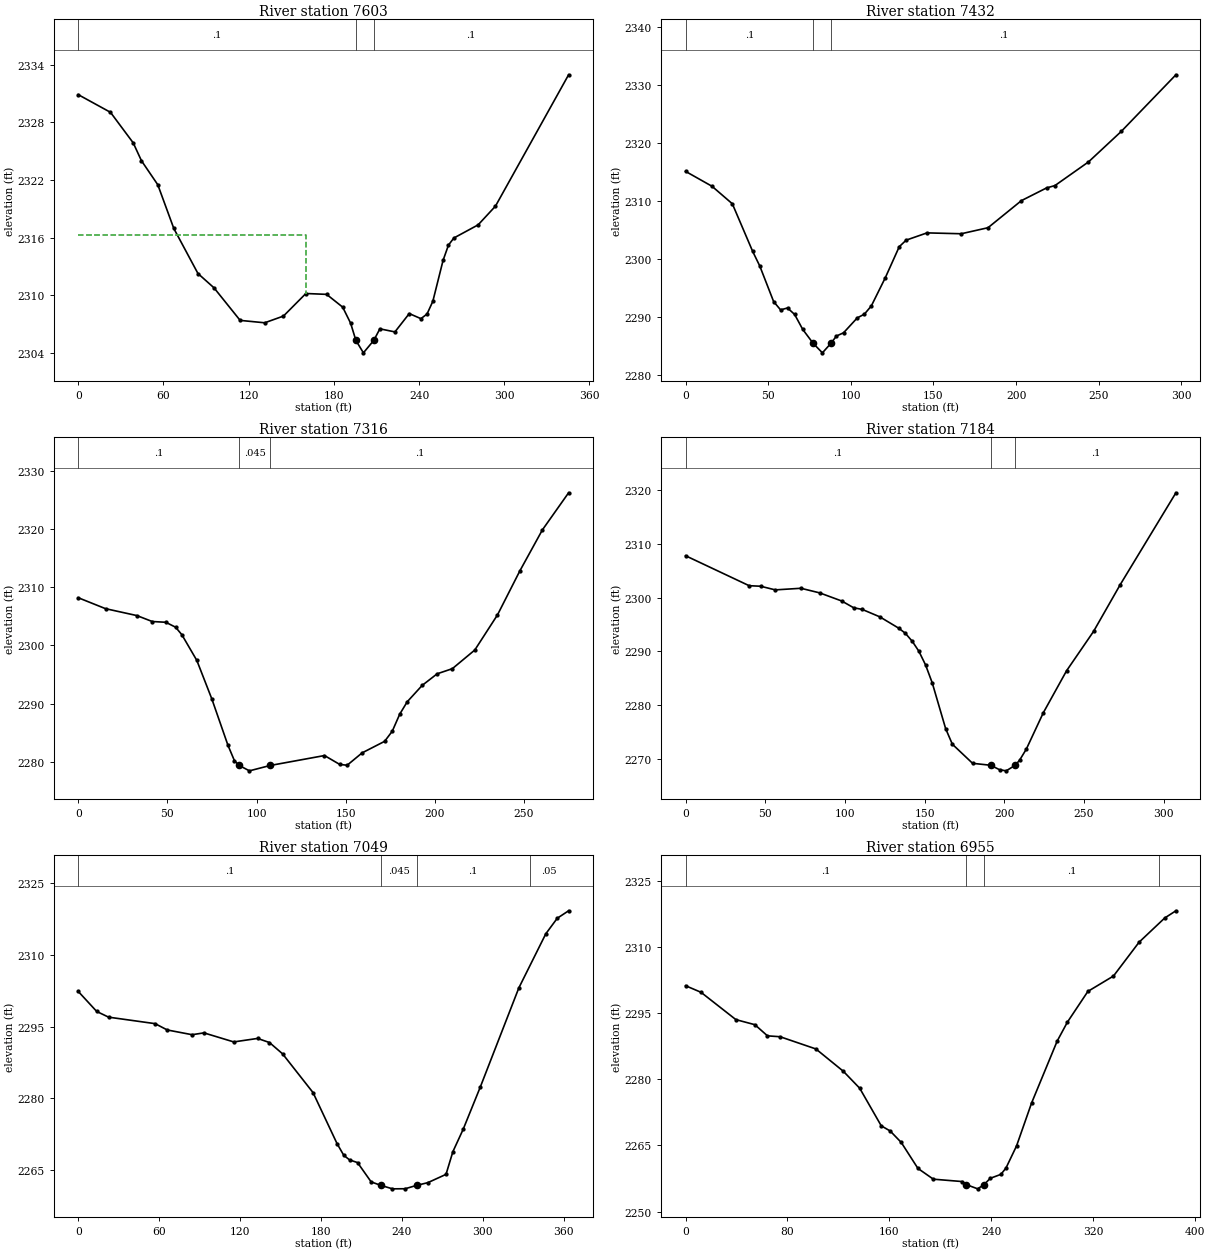
Type RM Length L Ch R = 1 ,7603    ,176.5,171.1,164.4
XS GIS Cut Line= 3
2254028.61419904669798.3976876262253835.36548673669983.217281727
2253849.54748428670059.819117957
#Sta/Elev= 30
       0 2330.89    22.7 2329.05    38.7 2325.87    44.5 2324.01      56 2321.51
    67.3 2316.95    84.3 2312.26    95.6 2310.77     114 2307.38   131.3 2307.13
   144.5 2307.83   160.3 2310.18   174.9 2310.09   186.2 2308.76   191.8 2307.09
   195.52305.298   200.8    2304   208.12305.294   212.4  2306.5     223 2306.18
   233.1 2308.09   241.3 2307.56   245.6 2308.04   249.7 2309.37   256.9 2313.63
   260.7 2315.22   264.5 2315.96   281.6 2317.33   293.8 2319.28   345.3 2332.96
#Mann= 3 ,-1,0
       0      .1       0   195.5    .045       0   208.1      .1       0
#XS Ineff= 2 , 0
          160.49 2316.23
Permanent Ineff=
       F       F
Bank Sta=195.5,208.1
XS Rating Curve= 0 ,0
Exp/Cntr(USF)=0,0
Exp/Cntr=0.3,0.1

Type RM Length L Ch R = 1 ,7432    ,115.9,115.9,115.9
XS GIS Cut Line= 4
2253741.84215932669773.5051153032253749.49960677669810.150962707
2253787.00265535669921.494466248 2253809.8192712 670061.39137623
#Sta/Elev= 30
       0 2315.11      16 2312.54    28.3 2309.52    40.6 2301.31    44.9 2298.79
    53.3 2292.64    57.5 2291.22    61.7 2291.55      66 2290.43    70.9 2287.85
   77.242285.437    82.8 2283.81   87.922285.438    91.3 2286.71    95.6 2287.27
   103.9 2289.84   108.2 2290.48   112.4  2291.9   120.9 2296.79   129.3 2302.12
   133.5 2303.25   146.1  2304.5   166.8 2304.35     183 2305.39   203.2 2310.06
   218.4 2312.25   223.5 2312.66   243.8 2316.74   263.7 2322.02   296.7 2331.77
#Mann= 3 ,-1,0
       0      .1       0   77.24    .045       0   87.92      .1       0
Bank Sta=77.24,87.92
XS Rating Curve= 0 ,0
Exp/Cntr=0.3,0.1

Type RM Length L Ch R = 1 ,7316    ,127.4,131.5,136.6
XS GIS Cut Line= 3
2253669.22775194669800.5578204692253639.19119939669844.822213696
2253708.74953161 670055.07808152
#Sta/Elev= 30
       0 2308.21    15.3 2306.33    32.9 2305.14    41.5 2304.12    49.1 2303.99
    54.6 2303.14    58.1 2301.85    66.5 2297.43    74.9 2290.82      84  2282.8
    87.6 2280.18    90.3 2279.36      96 2278.44   107.6 2279.36   138.1 2281.07
   146.6 2279.55   150.8  2279.4   159.2 2281.53   171.8 2283.51   176.1 2285.25
   180.3 2288.19   184.5 2290.32   192.9 2293.14   201.3 2295.13   209.8 2296.01
   222.4 2299.22   235.1 2305.25   247.7 2312.85   260.3 2319.88     275 2326.26
#Mann= 3 ,-1,0
       0      .1       0    90.3    .045       0   107.6      .1       0
Bank Sta=90.3,107.6
XS Rating Curve= 0 ,0
Exp/Cntr(USF)=0,0
Exp/Cntr=0.3,0.1

Type RM Length L Ch R = 1 ,7184    ,126.8,135.5,137.3
XS GIS Cut Line= 3
2253657.37121804 669795.815206912253565.68068922669881.182250989
 2253507.9788909670054.287645927
#Sta/Elev= 30
       0 2307.82    39.9 2302.24    47.1 2302.14    56.3 2301.46    72.4 2301.76
    84.2  2300.9      98 2299.39   105.5 2298.13   110.9 2297.82   121.9 2296.44
   133.7 2294.34   137.9 2293.39   142.3 2291.87   146.4 2290.04   150.6 2287.49
   154.8 2284.14   163.2 2275.63   167.4 2272.73   180.1 2269.17  191.482268.808
     197 2267.98   201.2 2267.77  206.862268.806   209.6 2269.75   213.8  2271.8
   224.5 2278.59   239.1 2286.41     256 2293.72   272.8 2302.46   307.7 2319.54
#Mann= 3 ,-1,0
       0      .1       0  191.48    .045       0  206.86      .1       0
Bank Sta=191.48,206.86
XS Rating Curve= 0 ,0
Exp/Cntr(USF)=0,0
Exp/Cntr=0.3,0.1

Type RM Length L Ch R = 1 ,7049    ,90.8,93.3,96.9
XS GIS Cut Line= 3
2253539.59631464669712.8194696112253477.94233836669844.031778102
2253344.35872308 670017.13717304
#Sta/Elev= 30
       0 2302.39    13.7  2298.2    22.5 2297.01      57 2295.65      66 2294.33
    84.4 2293.34    93.2 2293.72   115.3 2291.83     133 2292.56   141.8  2291.7
   151.5 2289.34   174.1 2281.23   191.9 2270.56   196.9 2268.11   201.2 2267.15
   207.1 2266.59   217.2 2262.55  224.492261.819     233  2261.1   242.4 2261.12
  250.832261.817   259.2 2262.39   272.7 2264.13   277.8 2268.88   285.4 2273.54
     298 2282.31   326.7 2303.13   346.7 2314.45   355.2  2317.7   363.6 2319.26
#Mann= 4 ,-1,0
       0      .1       0  224.49    .045       0  250.83      .1       0
  334.98     .05       0
Bank Sta=224.49,250.83
XS Rating Curve= 0 ,0
Exp/Cntr(USF)=0,0
Exp/Cntr=0.3,0.1

Type RM Length L Ch R = 1 ,6955    ,50.1,44.5,35
XS GIS Cut Line= 4
2253503.33403696669709.3111000352253408.69309802669838.366925859
2253334.27090513669871.061068401 2253319.6445782670013.882848979
#Sta/Elev= 30
       0 2301.22    12.1 2299.73    39.5 2293.53    54.4 2292.38    64.3 2289.85
    74.2 2289.65   102.3 2286.88   123.8 2281.83   136.7 2277.97   153.6 2269.45
   160.6 2268.28   169.3 2265.68   182.4 2259.79   194.5 2257.35   217.2 2256.81
   220.2 2256.14   229.3 2255.16  234.28 2256.13   239.2 2257.55   247.5 2258.44
   251.5 2259.87   259.8 2264.89   271.6 2274.62   291.7 2288.67   299.7 2292.95
   315.8 2299.93   335.9 2303.42     356 2311.09   376.1 2316.57   384.9 2318.21
#Mann= 4 ,-1,0
       0      .1       0   220.2    .045       0  234.28      .1       0
  371.33     .05       0
Bank Sta=220.2,234.28
XS Rating Curve= 0 ,0
Exp/Cntr(USF)=0,0
Exp/Cntr=0.3,0.1

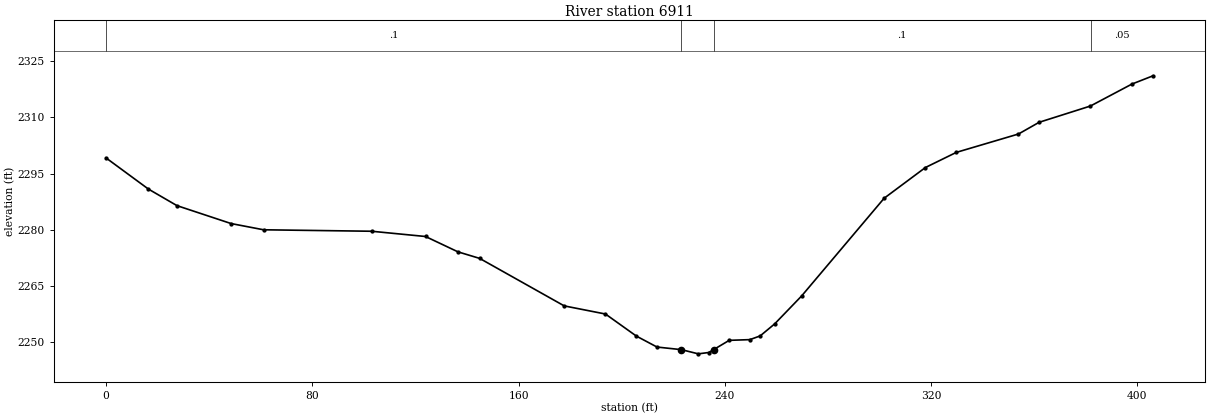
Type RM Length L Ch R = 1 ,6911    ,160.9,161,160.1
XS GIS Cut Line= 3
 2253362.4686042669622.9001199332253314.14399401669777.536426323
2253303.03062979 670021.34567896
#Sta/Elev= 30
       0 2299.17    16.4 2290.88    27.5 2286.45    48.5 2281.67    61.1 2280.01
     103 2279.62   123.9 2278.22   136.5 2274.12   144.9 2272.38   177.7 2259.71
   193.7 2257.54   205.7 2251.65   213.7 2248.73  223.152248.037   229.7 2246.92
   233.7 2247.27  235.632248.039   241.7 2250.52   249.7 2250.71   253.7  2251.7
   259.3 2254.89   269.8 2262.37   301.8 2288.43   317.8 2296.62   329.8 2300.66
   353.9 2305.56   361.9 2308.68   381.8 2313.02   397.9 2318.88   406.1 2321.09
#Mann= 4 ,-1,0
       0      .1       0  223.15    .045       0  235.63      .1       0
  382.01     .05       0
Bank Sta=223.15,235.63
XS Rating Curve= 0 ,0
Exp/Cntr=0.3,0.1