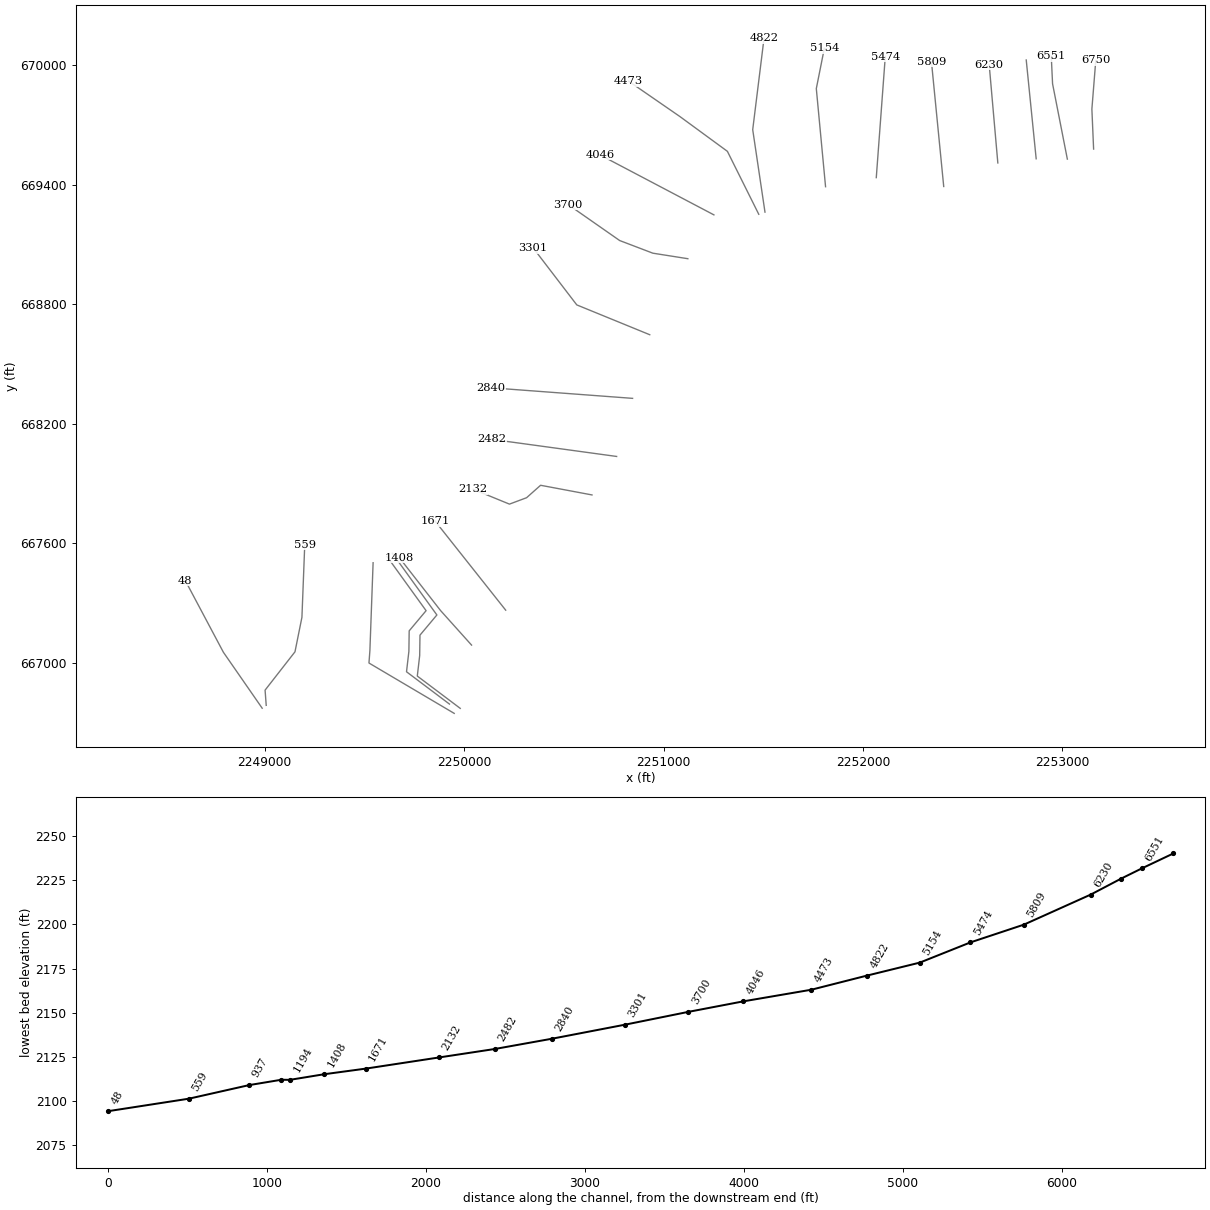
HEC-RAS study CASSITYFK_US.prj: CASSITYFK_US

--- CASSITYFK_US.g01 (geometry) --- (continued)

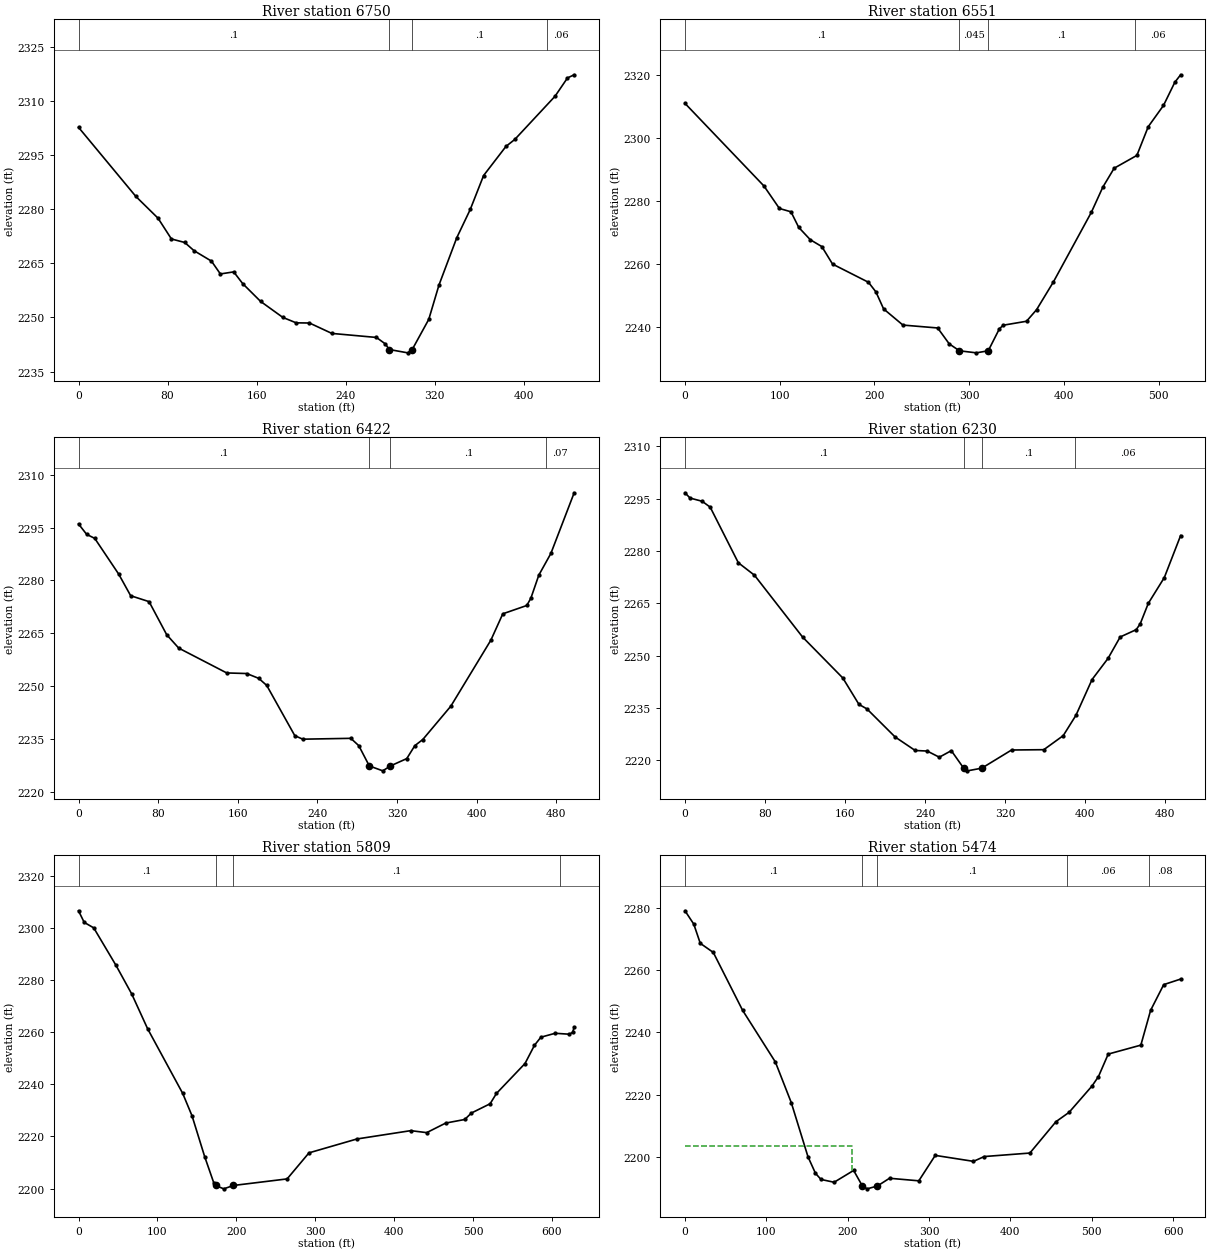
Type RM Length L Ch R = 1 ,6750    ,195,198.6,200.3
XS GIS Cut Line= 3
2253156.96924592669577.7646532652253148.29505559 669778.35530452
2253167.81198382670022.316907397
#Sta/Elev= 30
       0 2302.67    51.5 2283.54    71.5 2277.49    83.5 2271.75    95.5 2270.77
   103.8 2268.51   119.5 2265.61   127.5 2262.06   139.5 2262.63   147.6 2259.37
   163.6 2254.47   183.6 2250.03   195.6 2248.52   207.6 2248.47   227.7 2245.59
   267.8 2244.47   275.8 2242.67  279.332241.131   295.9 2240.21  299.94 2241.13
   314.8 2249.47     324    2259     340  2272.1   352.1 2279.92   364.1 2289.32
   384.2 2297.38   392.2 2299.33   428.3 2311.27   439.5 2316.35   445.5 2317.22
#Mann= 4 ,-1,0
       0      .1       0  279.33    .045       0  299.94      .1       0
  420.78     .06       0
Bank Sta=279.33,299.94
XS Rating Curve= 0 ,0
Exp/Cntr(USF)=0,0
Exp/Cntr=0.3,0.1

Type RM Length L Ch R = 1 ,6551    ,131.1,129.4,127.4
XS GIS Cut Line= 3
2253025.24429718 669527.357878262252951.12809357669905.114629455
2252944.60539075670043.291503981
#Sta/Elev= 30
       0 2310.88    83.4 2284.66    99.7 2277.53   111.9 2276.48   120.1 2271.53
   132.3 2267.62   144.5 2265.44   155.8 2259.89   193.7 2254.12   201.6 2251.06
   209.7 2245.67   230.1 2240.54   266.8 2239.62     279 2234.57  289.772232.376
   307.6 2231.73  320.172232.377     332 2239.39   336.1  2240.5   360.6 2241.75
   371.2 2245.42     389 2254.24   429.1 2276.35   441.1 2284.27   453.1  2290.3
   477.1 2294.37   489.1 2303.48   505.2 2310.22   517.2 2317.59   523.3 2319.95
#Mann= 4 ,-1,0
       0      .1       0  289.77    .045       0  320.17      .1       0
  474.96     .06       0
Bank Sta=289.77,320.17
XS Rating Curve= 0 ,0
Exp/Cntr=0.3,0.1

Type RM Length L Ch R = 1 ,6422    ,191.8,191.6,191.8
XS GIS Cut Line= 2
2252868.92252332669528.9996189162252819.04592895670024.512741204
#Sta/Elev= 30
       0 2296.01     8.2 2293.05    16.3 2291.92    40.4 2281.77    52.4 2275.65
    70.9 2273.97    88.6 2264.59   100.7 2260.79   148.9 2253.75     169 2253.58
   181.1 2252.21   189.1 2250.21   217.3 2235.96   225.3 2234.96   273.6  2235.2
   281.6 2233.12  292.172227.373   305.7 2225.98  313.382227.371   329.8 2229.45
   337.9 2233.12   345.9 2234.86   374.1 2244.33   414.3 2263.04   426.3 2270.52
   450.4 2272.88   454.5 2274.95   462.5  2281.5   474.6 2287.64     498 2304.85
#Mann= 4 ,-1,0
       0      .1       0  292.17    .045       0  313.38      .1       0
     470     .07       0
Bank Sta=292.17,313.38
XS Rating Curve= 0 ,0
Exp/Cntr(USF)=0,0
Exp/Cntr=0.3,0.1

Type RM Length L Ch R = 1 ,6230    ,416.9,421,414.1
XS GIS Cut Line= 2
2252676.60361025669508.0854174842252633.23265863670001.429992191
#Sta/Elev= 30
       0 2296.71     5.1 2295.19    17.2 2294.27    25.2 2292.58    53.3 2276.63
    69.4 2273.06   117.5 2255.31   157.7 2243.56   173.8 2235.99   181.8 2234.69
   209.9 2226.65     230 2222.76     242  2222.6   254.1 2220.83   266.1 2222.71
   278.42217.704   282.2 2216.92  296.55 2217.69   326.3  2222.9   358.5 2222.99
   377.9 2227.02   390.6 2232.85   406.7 2243.12   422.7  2249.2   434.8 2255.33
   450.8 2257.43   454.8 2259.09   462.9 2264.98   478.9 2272.38   495.2 2284.44
#Mann= 4 ,-1,0
       0      .1       0   278.4    .045       0  296.55      .1       0
     390     .06       0
Bank Sta=278.4,296.55
XS Rating Curve= 0 ,0
Exp/Cntr(USF)=0,0
Exp/Cntr=0.3,0.1

Type RM Length L Ch R = 1 ,5809    ,336.4,335.7,331.5
XS GIS Cut Line= 2
2252405.25509704669390.0027612562252343.79468926670015.199161327
#Sta/Elev= 30
       0 2306.53     7.2 2302.08    19.3 2299.97    47.4 2285.65    67.5 2274.58
    87.6 2261.27     132 2236.51   143.9 2227.86   159.9 2212.22   171.7 2201.94
  173.662201.158   184.1 2199.87  196.272201.159   264.4 2203.68   292.1 2213.67
   352.9    2219   421.1 2222.19   441.3 2221.43   465.4  2225.1   489.5 2226.47
   497.9 2228.94   521.7 2232.51   529.7 2236.46   565.9 2247.94   577.9 2254.94
     586 2258.03   604.1 2259.54   622.2 2259.18   626.2 2259.91   628.2 2261.83
#Mann= 4 ,-1,0
       0      .1       0  173.66    .045       0  196.27      .1       0
     610     .06       0
Bank Sta=173.66,196.27
XS Rating Curve= 0 ,0
Exp/Cntr=0.3,0.1

Type RM Length L Ch R = 1 ,5474    ,315.8,319.2,319
XS GIS Cut Line= 2
2252067.02890104669434.4261728862252112.22022333670041.909528291
#Sta/Elev= 30
       0 2278.95    10.8 2274.68    18.8 2268.52    34.8  2265.6    70.8 2247.06
   111.1 2230.48   130.6  2217.5   151.2  2200.1   160.4  2194.8   167.2 2192.84
   183.3 2191.94   207.3 2195.73  218.032190.743   223.9 2189.83  236.512190.742
   251.4 2193.22   287.4  2192.4   307.6 2200.55   354.6 2198.64   367.8 2200.18
   423.9  2201.3     456 2211.36   472.1 2214.35   500.2 2222.76   508.2 2225.81
   520.2 2233.02   560.3 2235.89   572.3 2247.04   588.4 2255.28   609.2 2257.06
#Mann= 5 ,-1,0
       0      .1       0  218.03    .045       0  236.51      .1       0
     470     .06       0     570     .08       0
#XS Ineff= 2 , 0
          205.72 2203.48
Permanent Ineff=
       F       F
Bank Sta=218.03,236.51
XS Rating Curve= 0 ,0
Exp/Cntr=0.3,0.1

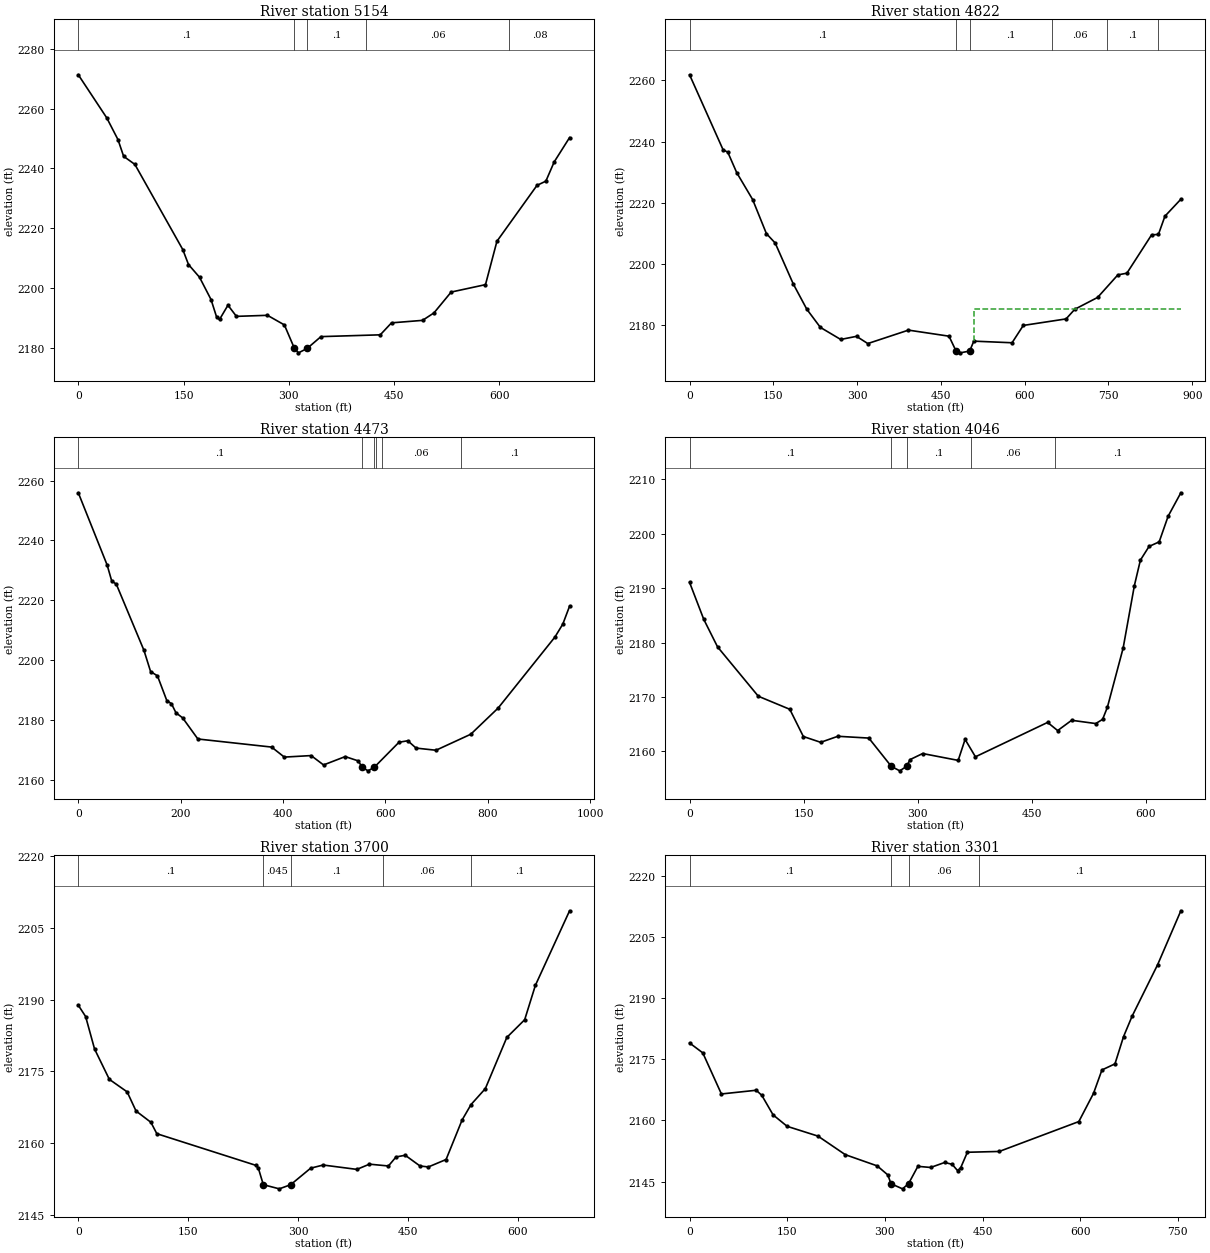
Type RM Length L Ch R = 1 ,5154    ,335,332.6,331.6
XS GIS Cut Line= 3
2251812.68318765 669388.90662804 2251766.2929235669881.006443595
2251806.46014876670082.692661148
#Sta/Elev= 30
       0 2271.28    40.5  2256.9    56.5 2249.63    64.6 2244.03    80.6 2241.33
   148.9 2212.85     157 2207.87   172.7 2203.62   189.1 2196.17   197.1 2190.28
   201.2 2189.51   213.2 2194.27   225.3 2190.55   269.5  2190.9   293.6 2187.69
  307.932179.829   313.7 2178.36  326.032179.829   345.7 2183.78   430.2 2184.38
   446.2 2188.38   490.4 2189.21   506.7 2191.71   531.2 2198.67   580.1 2201.15
   596.4 2215.64   653.5 2234.33   666.1 2235.73     678 2242.17   699.9  2250.3
#Mann= 5 ,-1,0
       0      .1       0  307.93    .045       0  326.03      .1       0
     410     .06       0  614.28     .08       0
Bank Sta=307.93,326.03
XS Rating Curve= 0 ,0
Exp/Cntr=0.3,0.1

Type RM Length L Ch R = 1 ,4822    ,337.9,348.4,362.2
XS GIS Cut Line= 3
2251508.88177667669261.5502271852251447.34995919669675.070275705
2251504.08100578670133.066093186
#Sta/Elev= 30
       0 2261.82    60.1 2237.29    68.4 2236.55    84.5 2229.83   112.9 2221.08
   137.6 2209.93   153.3 2206.87   185.7 2193.49   209.9 2185.25   234.2 2179.31
   270.6 2175.37   298.9 2176.39   319.1 2174.03   391.9 2178.42   464.5 2176.44
  477.152171.588   484.7    2171  501.512171.589   508.9 2174.82   577.4 2174.29
   597.5 2179.95   674.1 2182.08   689.7 2185.23   730.6  2189.1   766.8 2196.46
     783 2197.02   827.3 2209.56   839.4 2209.66   851.1 2215.63   879.6 2221.17
#Mann= 6 ,-1,0
       0      .1       0  477.15    .045       0  501.51      .1       0
  648.07     .06       0  748.07      .1       0  838.07     .08       0
#XS Ineff= 2 , 0
                          509.78         2185.21
Permanent Ineff=
       F       F
Bank Sta=477.15,501.51
XS Rating Curve= 0 ,0
Exp/Cntr=0.3,0.1

Type RM Length L Ch R = 1 ,4473    ,426,427.8,428.9
XS GIS Cut Line= 4
2251477.72613593669250.717180592 2251320.3824894669566.392549483
2251082.65363195669740.5165996972250825.24377282669918.138867927
#Sta/Elev= 30
       0 2255.94    56.4 2231.79    65.3 2226.48    74.3  2225.4   128.3  2203.3
   141.3  2196.2   154.7 2194.77     173  2186.5     182 2185.47   190.9 2182.42
   203.9 2180.73   233.7 2173.67   377.8 2170.97   402.6 2167.62     455 2168.13
   479.3    2165   521.6 2167.79     547 2166.36  554.842164.224   566.2 2163.03
  578.412164.227   626.7 2172.58   643.9 2173.08   660.1 2170.63     699 2169.91
     767 2175.26   820.5 2184.01   931.5 2207.74   946.9 2212.07   960.1 2218.06
#Mann= 6 ,-1,0
       0      .1       0  554.84    .045       0  578.41      .1       0
  582.72     .07       0  592.72     .06       0  747.39      .1       0
Bank Sta=554.84,578.41
XS Rating Curve= 0 ,0
Exp/Cntr=0.3,0.1

Type RM Length L Ch R = 1 ,4046    ,340.1,346,345.3
XS GIS Cut Line= 2
 2251252.7610867669247.7186049482250681.08265708669548.649323082
#Sta/Elev= 30
       0 2191.07    18.7 2184.27    36.8 2179.22    90.4 2170.15   131.8 2167.75
   149.6 2162.75   172.4 2161.68     195 2162.79   235.7 2162.46  265.31 2157.26
   276.4 2156.44   285.4 2157.27     290 2158.51   306.5 2159.62   353.2 2158.36
   362.3 2162.22   375.9 2159.02   470.8 2165.34     484 2163.84   502.4 2165.73
   534.1 2165.13   543.1  2165.9   549.4 2168.12   570.1 2178.99   584.9 2190.49
   592.8 2195.16   604.2 2197.68   617.5 2198.52   629.3 2203.24     646 2207.54
#Mann= 5 ,-1,0
       0      .1       0  265.31    .045       0   285.4      .1       0
     370     .06       0     480      .1       0
Bank Sta=265.31,285.4
XS Rating Curve= 0 ,0
Exp/Cntr(USF)=0,0
Exp/Cntr=0.3,0.1

Type RM Length L Ch R = 1 ,3700    ,399.4,398.2,395.5
XS GIS Cut Line= 4
2251122.05810282 669027.911454372250946.53554756669055.604555262
2250780.23892508669118.9721617552250521.89318252669299.271506743
#Sta/Elev= 30
       0  2188.8      10 2186.45    22.2 2179.67    42.4 2173.33    66.7 2170.72
    78.8 2166.73    99.1 2164.37   107.2 2161.99   242.7 2155.37   245.8  2154.8
   252.62151.344   274.4 2150.48  289.942151.344   317.2 2154.79   334.3 2155.45
   380.3 2154.54   397.5 2155.63   423.4 2155.25   433.8 2157.14   446.3 2157.49
   466.5 2155.25   477.9 2155.05   502.1  2156.6   523.9 2164.83   536.2 2168.08
   555.7  2171.4     585 2182.08   609.4 2185.78     624 2192.95   670.7 2208.52
#Mann= 5 ,-1,0
       0      .1       0   252.6    .045       0  289.94      .1       0
  415.65     .06       0  535.65      .1       0
Bank Sta=252.6,289.94
XS Rating Curve= 0 ,0
Exp/Cntr=0.3,0.1

Type RM Length L Ch R = 1 ,3301    ,457.3,461.6,465.6
XS GIS Cut Line= 3
 2250930.9350543 668646.673454372250565.06086985668796.242912594
2250346.65309126669081.598776668
#Sta/Elev= 30
       0 2179.01    20.3 2176.58    48.9  2166.5   102.4 2167.41     111 2166.15
   128.3 2161.37   149.9 2158.56   197.3 2156.16   239.2 2151.61   288.2 2148.86
   304.6 2146.63  309.362144.484   327.1 2143.23  336.282144.481   350.7 2148.75
   370.3 2148.47   391.9  2149.7   403.3 2149.24   411.6 2147.71   416.5 2148.42
   426.7  2152.2   475.7  2152.4   597.9 2159.73   620.5 2166.66   633.4 2172.39
   653.4 2173.88   666.6 2180.58   679.7 2185.57     719 2198.23   754.6 2211.43
#Mann= 4 ,-1,0
       0      .1       0  309.36    .045       0  336.28     .06       0
  445.27      .1       0
Bank Sta=309.36,336.28
XS Rating Curve= 0 ,0
Exp/Cntr=0.3,0.1

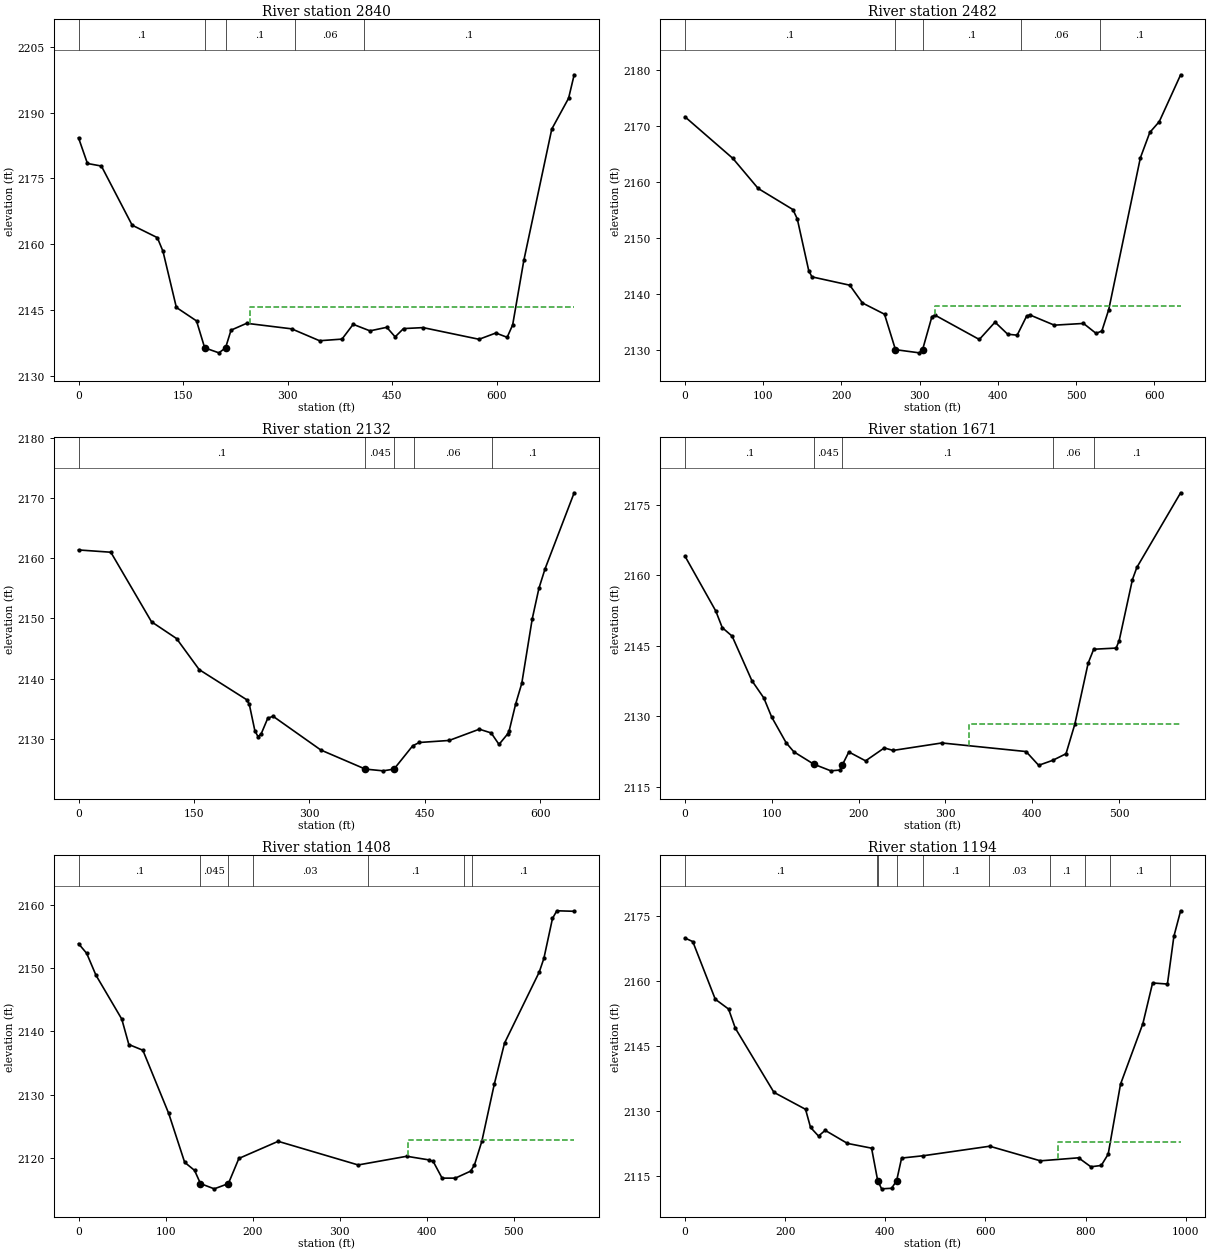
Type RM Length L Ch R = 1 ,2840    ,354.8,357.3,357.6
XS GIS Cut Line= 2
2250844.90758072668327.5518631212250136.15365598668380.503422921
#Sta/Elev= 30
       0 2184.26    12.8  2178.4    32.8 2177.82    76.9 2164.34     113  2161.5
   121.1 2158.39   140.3 2145.59   169.2 2142.52  180.932136.377   201.3 2135.24
  210.832136.376   218.7 2140.41   241.1 2141.97   305.6 2140.71   345.6    2138
   377.8 2138.37   393.8 2141.74   417.9 2140.25     442 2141.06     454 2138.88
     466 2140.77   494.1 2140.99   574.3 2138.33   598.4 2139.76   614.6 2138.78
   622.5  2141.6   638.5 2156.29   678.6 2186.25   702.7 2193.27   710.7 2198.62
#Mann= 5 ,-1,0
       0      .1       0  180.93    .045       0  210.83      .1       0
     310     .06       0     410      .1       0
#XS Ineff= 2 , 0
                          245.27         2145.59
Permanent Ineff=
       F       F
Bank Sta=180.93,210.83
XS Rating Curve= 0 ,0
Exp/Cntr=0.3,0.1

Type RM Length L Ch R = 1 ,2482    ,344.3,350.5,363.4
XS GIS Cut Line= 2
2250764.94554857668036.1934589132250137.10146692668122.179395394
#Sta/Elev= 30
       0 2171.68    61.3 2164.23    93.6 2158.86     138 2155.09   143.6 2153.41
   158.2 2144.18   162.3 2143.05   210.7 2141.56   226.9 2138.38   255.1 2136.37
  269.11 2130.03   299.5 2129.46   303.8 2130.04   315.7 2135.93   319.7  2136.2
   376.3 2131.85   396.4 2134.95   412.6 2132.79   424.7 2132.62   436.8 2136.03
   440.8 2136.25   472.2 2134.41   509.5 2134.72   525.6 2132.94     533 2133.37
   541.8 2137.21   582.2 2164.33   594.3 2168.89   606.4 2170.82   633.7  2179.2
#Mann= 5 ,-1,0
       0      .1       0  269.11    .045       0   303.8      .1       0
     430     .06       0     530      .1       0
#XS Ineff= 2 , 0
                          320.07         2137.86
Permanent Ineff=
       F       F
Bank Sta=269.11,303.8
XS Rating Curve= 0 ,0
Exp/Cntr=0.3,0.1

Type RM Length L Ch R = 1 ,2132    ,482.3,461.4,438.5
XS GIS Cut Line= 5
2250641.40647803667843.222192782 2250383.5763519667891.657322825
2250313.27459543667829.2259651562250227.33403868667797.173747958
2250045.72433633 667871.54241032
#Sta/Elev= 30
       0 2161.38      42    2161    94.9 2149.44   127.4 2146.66   156.9 2141.49
   218.6 2136.49     222 2135.73   229.2 2131.36   233.2 2130.37   237.3 2130.77
     246 2133.41   252.9 2133.74     315 2128.13   372.8 2124.96     396 2124.67
   410.1 2124.96   434.4 2128.83   442.9 2129.38   481.8 2129.72     521 2131.59
   536.4 2130.97   546.6 2129.06   557.8 2130.79   559.6 2131.21   568.2 2135.76
   576.2 2139.21   589.8 2149.93   598.5 2155.01   606.4 2158.22   644.3 2170.88
#Mann= 5 ,-1,0
       0      .1       0   372.8    .045       0   410.1      .1       0
  436.36     .06       0  538.08      .1       0
Bank Sta=372.8,410.1
XS Rating Curve= 0 ,0
Exp/Cntr(USF)=0,0
Exp/Cntr=0.3,0.1

Type RM Length L Ch R = 1 ,1671    ,259.6,262.2,262
XS GIS Cut Line= 2
2250208.54728236667265.3247765712249853.96799154667712.688423334
#Sta/Elev= 30
       0 2164.08    35.5 2152.39    42.9 2148.86    54.3 2147.04      77 2137.57
    90.8 2133.87    99.8 2129.82   116.5 2124.32   125.4 2122.39   148.32119.762
     168 2118.34   178.5 2118.51   181.42119.673   188.7 2122.36     208 2120.47
   229.5 2123.22   239.7 2122.69   295.8 2124.28   392.8 2122.45   407.3 2119.52
   423.5 2120.58   438.8 2121.98     449 2128.31   464.3 2141.29   470.7 2144.25
   496.5  2144.5     500 2146.06   515.3  2159.1   520.4 2161.69   570.8 2177.59
#Mann= 5 ,-1,0
       0      .1       0   148.3    .045       0   181.4      .1       0
   423.5     .06       0   470.7      .1       0
#XS Ineff= 2 , 0
                          326.83         2128.24
Permanent Ineff=
       F       F
Bank Sta=148.3,181.4
XS Rating Curve= 0 ,0
Exp/Cntr=0.3,0.1

Type RM Length L Ch R = 1 ,1408    ,225.9,214.5,198.7
XS GIS Cut Line= 3
  2250037.354015667090.1796141682249882.08079609 667263.19940569
2249674.98450209667528.846484378
#Sta/Elev= 30
       0 2153.85     9.4 2152.32      20 2148.88    49.7 2141.94    57.8 2137.93
    73.9 2137.03   103.6 2127.05   121.9 2119.34   133.3 2118.06  140.092115.977
   155.9 2115.15  172.122115.975   184.2 2119.95   229.3 2122.65   321.2 2118.92
     377 2120.29   402.4 2119.72   407.4 2119.47   417.6 2116.84   432.8 2116.84
   450.3 2117.94   454.7 2118.89   463.3 2122.68   477.5 2131.64   489.3 2138.15
   529.2 2149.37   534.5 2151.52   544.4 2157.83   549.4 2159.04   569.3 2158.96
#Mann= 7 ,-1,0
       0      .1       0  140.09    .045       0  172.12      .1       0
     200     .03       0  332.48      .1       0  442.48     .03       0
  452.48      .1       0
#XS Ineff= 2 , 0
                           378.4          2122.8
Permanent Ineff=
       F       F
Bank Sta=140.09,172.12
XS Rating Curve= 0 ,0
Exp/Cntr(USF)=0,0
Exp/Cntr=0.3,0.1

Type RM Length L Ch R = 1 ,1194    ,55.4,54.4,54.6
XS GIS Cut Line= 6
2249980.62879286666772.8339222472249765.28231122666934.841252461
2249777.18106338667037.467989839 2249778.6684074667140.094727217
2249863.44701654667241.2341205752249640.30640814 667550.55831196
#Sta/Elev= 30
       0 2170.01    15.6 2169.19    60.5 2155.86    87.1 2153.58   100.5 2149.16
   177.7 2134.31   240.8 2130.39   250.8  2126.2   266.7  2124.2     280 2125.52
   324.5  2122.5   372.7  2121.4  384.932113.885   392.7 2111.99   412.7 2112.12
  422.742113.883   432.7 2119.11   476.3 2119.65   608.6 2121.85   709.9 2118.47
   786.1 2119.17   810.7 2117.09   831.5  2117.4   845.3 2120.02   869.9 2136.19
   914.6 2150.22     934 2159.62   963.6 2159.37   976.5 2170.39     990 2176.32
#Mann= 10 ,-1,0
       0      .1       0  382.95     .08       0  384.93    .045       0
  422.74     .08       0   476.3      .1       0  606.91     .03       0
  728.58      .1       0  798.58     .03       0  848.58      .1       0
  968.58     .06       0
#XS Ineff= 2 , 0
                          745.04         2122.73
Permanent Ineff=
       F       F
Bank Sta=384.93,422.74
XS Rating Curve= 0 ,0
Exp/Cntr=0.3,0.1

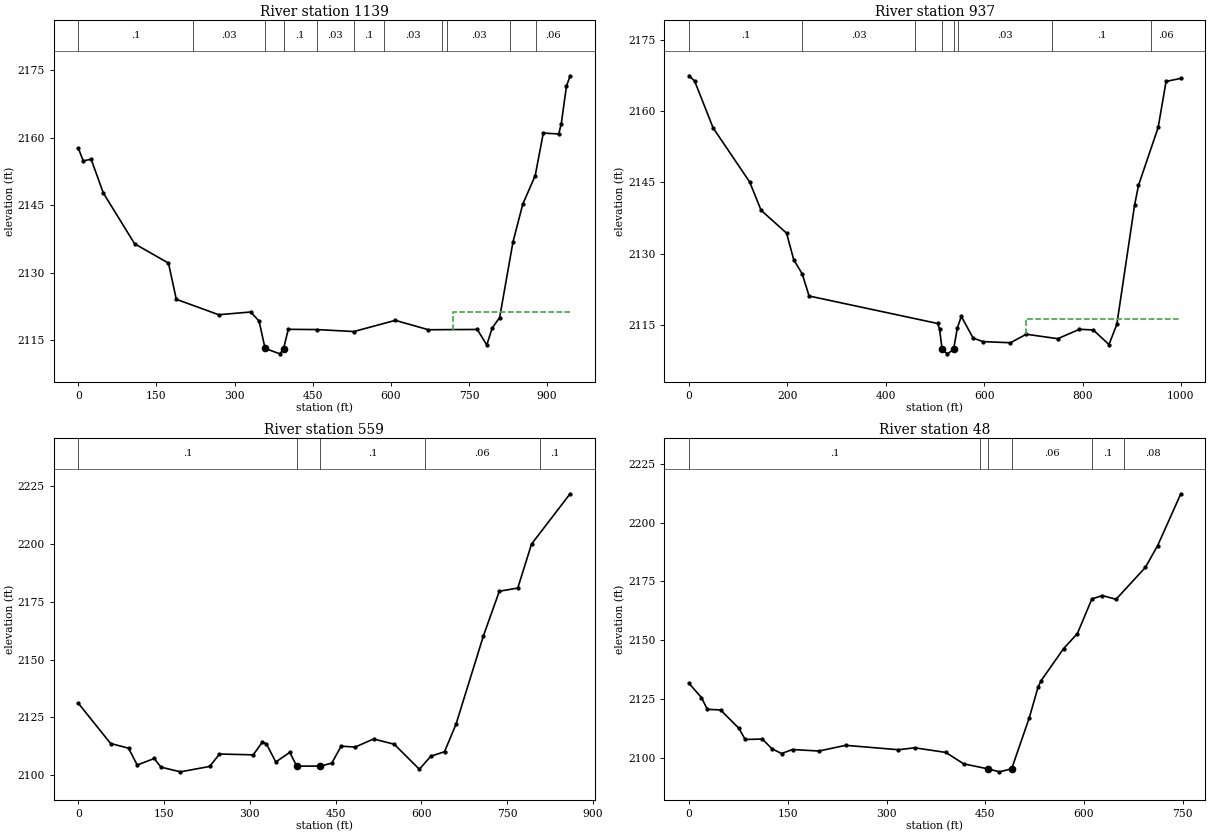
Type RM Length L Ch R = 1 ,1139    ,201,202.5,202.6
XS GIS Cut Line= 6
2249926.51943946 666794.365508942249711.17295782666956.372839154
2249723.07170998667058.999576532  2249724.559054 667161.62631391
2249809.33766314667262.765707268 2249612.9692471667534.906298154
#Sta/Elev= 30
       0 2157.69     9.4 2154.86    24.6 2155.22      48 2147.73   108.1 2136.46
   173.1 2132.17   188.1 2124.14   269.5 2120.71     331 2121.32   347.1 2119.28
  358.542113.224   387.1 2112.03     394 2113.17   403.1 2117.47   457.9 2117.42
   528.9 2116.98   608.6 2119.46   672.1 2117.38   765.9 2117.44   784.2    2114
   794.5 2117.73   808.9 2120.09   834.6 2136.92   853.3 2145.25   877.2  2151.6
   892.7 2161.04   922.3 2160.83   927.2  2163.1   937.1 2171.38   944.2 2173.75
#Mann= 11 ,-1,0
       0      .1       0     220     .03       0  358.54    .045       0
     394      .1       0   457.9     .03       0  529.06      .1       0
  586.91     .03       0  698.58      .1       0  708.58     .03       0
  828.58      .1       0  878.58     .06       0
#XS Ineff= 2 , 0
                          718.82         2121.24
Permanent Ineff=
       F       F
Bank Sta=358.54,394
XS Rating Curve= 0 ,0
Exp/Cntr=0.3,0.1

Type RM Length L Ch R = 1 ,937     ,377.5,378,376.4
XS GIS Cut Line= 4
2249950.33094337666747.7371220972249522.84523596 667000.28438934
2249527.48569668 667061.938504322249543.62735266 667503.23365598
#Sta/Elev= 30
       0 2167.42    11.4 2166.31      49 2156.47   123.3 2145.11   146.5 2139.16
   198.3 2134.36   212.9 2128.77   230.2 2125.78   244.1 2121.15   505.4 2115.38
   509.4 2114.17  514.622109.916   525.5    2109  537.862109.919   545.5 2114.41
   553.6 2116.88   577.6 2112.31   597.6 2111.57   653.6 2111.33   685.6 2113.12
   749.7 2112.18   793.7 2114.16   821.8 2114.02   853.8 2110.95   869.8  2115.2
   905.8 2140.19   913.8 2144.38   953.8 2156.56   969.9 2166.24   999.9 2166.87
#Mann= 8 ,-1,0
       0      .1       0     230     .03       0     460     .07       0
  514.62    .045       0  537.86     .07       0  546.51     .03       0
  738.34      .1       0  938.34     .06       0
#XS Ineff= 2 , 0
                          684.67         2116.23
Permanent Ineff=
       F       F
Bank Sta=514.62,537.86
XS Rating Curve= 0 ,0
Exp/Cntr=0.3,0.1

Type RM Length L Ch R = 1 ,559     ,490.7,510.5,516.6
XS GIS Cut Line= 5
2249007.54973137666788.0040923492249001.88521278666864.290219832
 2249151.8139618667056.4551023222249186.64948328667229.418632083
2249200.80312071667592.692548849
#Sta/Elev= 30
       0 2131.05    56.5  2113.6    87.8 2111.58     103 2104.28   132.9 2107.11
   144.3 2103.37   178.5 2101.32   229.8 2103.66   246.9 2109.04   305.9 2108.69
   322.1 2114.25   329.1 2113.39   345.4 2105.58   369.9 2109.78     382  2103.8
   423.4 2103.81   443.4 2105.09   459.7 2112.45   484.2 2112.06   516.4 2115.55
   552.5 2113.29   596.5 2102.44   616.5 2108.08   640.5 2110.04   660.6 2121.94
   708.6  2160.3   736.4  2179.6   768.6 2180.96   792.7 2200.03   860.2 2221.83
#Mann= 5 ,-1,0
       0      .1       0     382    .045       0   423.4      .1       0
  606.67     .06       0  806.67      .1       0
Bank Sta=382,423.4
XS Rating Curve= 0 ,0
Exp/Cntr=0.3,0.1

Type RM Length L Ch R = 1 ,48      ,,,
XS GIS Cut Line= 3
2248987.35181014666773.654393358 2248792.8001628667054.220399501
  2248602.439804667412.481775581
#Sta/Elev= 30
       0 2131.75    18.9 2125.73    27.8 2120.73    47.9 2120.48    75.8 2112.67
    85.3 2107.94   111.4 2108.12     126 2103.99   140.6 2101.98   157.2 2103.68
   197.4 2103.04   237.9 2105.46   318.1 2103.59   342.8 2104.41   390.1 2102.45
   417.2  2097.6  453.912095.489   471.6 2094.21  490.11 2095.49   516.9 2117.16
   530.4 2130.31     535 2132.95   568.9 2146.46     590 2152.91     612 2167.59
     628 2169.01   648.7 2167.42   693.1 2180.92   711.7 2190.09   747.1  2212.2
#Mann= 6 ,-1,0
       0      .1       0  441.42     .06       0  453.91    .045       0
  490.11     .06       0  611.42      .1       0  661.42     .08       0
Bank Sta=453.91,490.11
XS Rating Curve= 0 ,0
Exp/Cntr=0.3,0.1
LCMann Table=0

Chan Stop Cuts=-1
Use User Specified Reach Order=0
Composite Channel Slope=5